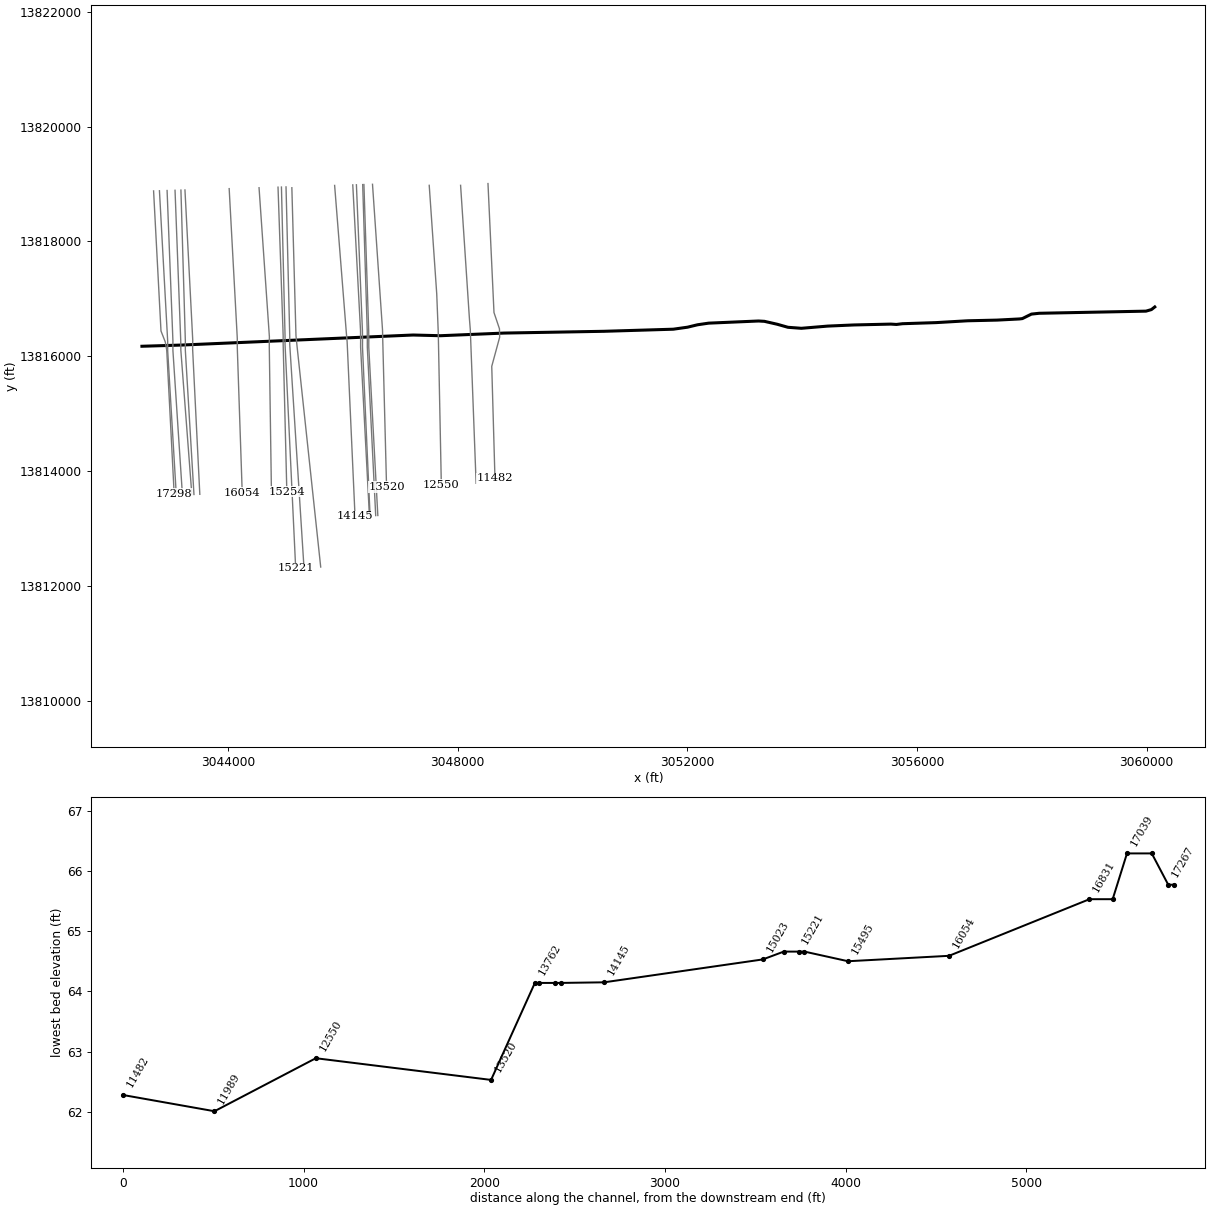
--- D122-00-00.prj (project) ---

Proj Title=D122-00-00
Current Plan=p06
Default Exp/Contr=.3,.1
English Units
Geom File=g04
Flow File=f02
Flow File=f05
Flow File=f04
Plan File=p02
Plan File=p06
Plan File=p05
Y Axis Title=Elevation
X Axis Title(PF)=Main Channel Distance
X Axis Title(XS)=Station
BEGIN DESCRIPTION:
Brays Bayou Watershed
Tributary 21.95
HCFCD Unit D122-00-00
Flood Hazard & Floodway Model
10, 2, 1, 0.2% Event
Filename D122.prj
Prepared by: Dodson & Associates, Inc.   Date: September 2003
Reviewed by:____________________	 Date:_________
STATUS (Final RAS, SVSQ)
FOR FLOOD HARZARD RECOVERY DATA ONLY,03/02/2004
Will Be Voided Upon Release of The Preliminary DFIRM
END DESCRIPTION:
DSS Export Rating Curves= 0
DSS Export Rating Curve Sorted= 0
DSS Export Volume Flow Curves= 0
DXF OffsetX= 0
DXF OffsetY= 0
DXF ScaleX= 1
DXF ScaleY= 10

--- D122-00-00.p06 (plan) ---

Plan Title=Floodway
Version=Version 3.0.1  Mar 2001
Short Identifier=Floodway0607
Geom File=g04
Flow File=f05
Subcritical Flow
K Sum by GR= 0
Std Step Tol= 0.01
Critical Tol= 0.01
Num of Std Step Trials= 20
Max Error Tol= 0.3
Flow Tol Ratio= 0.001
Split Flow NTrial= 30
Split Flow Tol= 0.02
Split Flow Ratio= 0.02
Log Output Level= 0
Friction Slope Method= 2
Unsteady Friction Slope Method= 2
Secant Critical Depth
Global Vel Dist= 0 , 0 , 0
Global Log Level= 0
CheckData=True
Encroach Param=-1 ,0,0, 2
Encroach River=D122-00-00
Encroach Reach=Reach 0
Encroach Node=17298
       1 2648.04 2765.17
Encroach Node=17267
       1 2634.04 2751.17
Encroach Node=17176
       1 2602.28  2782.3
Encroach Node=17108
       1 2602.28  2791.3
Encroach Node=17039
       1 2611.28  2791.3
Encroach Node=16960
       1 2621.32 2771.17
Encroach Node=16831
       1 2633.32 2783.17
Encroach Node=16054
       1 2623.47 2767.44
Encroach Node=15495
       1 2618.21 2734.77
Encroach Node=15254
       1 2605.35 2727.38
Encroach Node=15221
       1 2622.88 2729.94
Encroach Node=15180
       1 2612.88 2729.94
Encroach Node=15139
       1 2612.88 2719.94
Encroach Node=15023
       1 2591.64 2724.55
Encroach Node=14145
       1 2600.43 2732.06
Encroach Node=13904
       1 2583.59 2701.44
Encroach Node=13871
       1 2590.59 2708.44
Encroach Node=13829
       1 2580.59 2708.44
Encroach Node=13787
       1 2580.59 2698.44
Encroach Node=13762
       1 2582.59 2700.44
Encroach Node=13520
       1 2584.05 2715.81
Encroach Node=12550
       1 2553.53 2687.05
Encroach Node=11989
       1 2521.54 2650.32
Encroach Node=11482
       1 2564.37 2693.13
Encroach Node=11289
       1 2554.69 2668.16
Encroach Node=11198
       1 2545.69 2659.16
Encroach Node=11177
       1 2545.69 2673.16
Encroach Node=11155
       1 2559.69 2673.16
Encroach Node=11074
       1 2604.69 2718.16
Encroach Node=10707
       1 2622.99 2720.52
Encroach Node=10022
       1 2637.22 2736.43
Encroach Node=8814
       1 2651.47 2753.65
Encroach Node=8646
       1 2653.67 2753.57
Encroach Node=8551
       1  2629.7 2750.57
Encroach Node=8528
       1  2629.7 2754.57
Encroach Node=8505
       1 2654.67 2754.57
Encroach Node=8447
       1 2641.67 2741.57
Encroach Node=8293
       1 2645.58 2738.64
Encroach Node=7390
       1 2579.26 2682.74
Encroach Node=7139
       1 2579.26 2682.74
Encroach Node=7019
       1 2577.34 2681.46
Encroach Node=7014
       1 2577.34 2681.46
Encroach Node=7009
       1 2578.84 2681.46
Encroach Node=6889
       1 2594.34 2696.96
Encroach Node=6841
       1 2601.34 2703.96
Encroach Node=6155
       1 2713.97 2824.41
Encroach Node=5294
       1 2711.62 2826.84
Encroach Node=4773
       1 2732.13 2849.46
Encroach Node=4693
       1 2741.13 2858.46
Encroach Node=4586
       1 2736.66 2882.19
Encroach Node=4554
       1 2736.66 2882.19
Encroach Node=4522
       1 2738.16 2882.19
Encroach Node=4424
       1 2741.25 2885.69
Encroach Node=4331
       1 2736.97 2911.22
Encroach Node=3499
       1  2763.6 2920.11
Encroach Node=3411
       1  2756.6 2913.11
Encroach Node=3279
       1 2732.09 2886.03
Encroach Node=3231
       1 2732.09 2886.03
Encroach Node=3182
       1 2732.09 2871.03
Encroach Node=3068
       1 2723.34 2873.97
Encroach Node=2755
       1 2728.97 2885.79
Encroach Node=2036
       1 2707.64 2884.48
Encroach Node=1197
       1 2904.03 3079.82
Encroach Node=514
       1 3204.72 3334.71
Encroach Node=369
       1 3235.72 3365.71
Encroach Node=275
       1 3201.19 3417.88
Encroach Node=265
       1 3201.19 3417.88
Encroach Node=255
       1 3223.19 3417.88
Encroach Node=183
       1 3184.19 3378.88
Encroach Node=84
       1 3136.19 3330.88
Encroach Reach=D122-00-00_0001
Encroach Node=17298
       1 2648.04 2765.17
Encroach Node=17267
       1 2634.04 2751.17
Encroach Node=17176
       1 2602.28  2782.3
Encroach Node=17108
       1 2602.28  2791.3
Encroach Node=17039
       1 2611.28  2791.3
Encroach Node=16960
       1 2621.32 2771.17
Encroach Node=16831
       1 2633.32 2783.17
Encroach Node=16054
       1 2623.47 2767.44
Encroach Node=15495
       1 2618.21 2734.77
Encroach Node=15254
       1 2605.35 2727.38
Encroach Node=15221
       1 2622.88 2729.94
Encroach Node=15180
       1 2612.88 2729.94
Encroach Node=15139
       1 2612.88 2719.94
Encroach Node=15023
       1 2591.64 2724.55
Encroach Node=14145
       1 2600.43 2732.06
Encroach Node=13904
       1 2583.59 2701.44
Encroach Node=13871
       1 2590.59 2708.44
Encroach Node=13829
       1 2580.59 2708.44
Encroach Node=13787
       1 2580.59 2698.44
Encroach Node=13762
       1 2582.59 2700.44
Encroach Node=13520
       1 2584.05 2715.81
Encroach Node=12550
       1 2553.53 2687.05
Encroach Node=11989
       1 2521.54 2650.32
Encroach Node=11482
       1 2564.37 2693.13
Encroach Node=11289
       1 2554.69 2668.16
Encroach Node=11198
       1 2545.69 2659.16
Encroach Node=11177
       1 2545.69 2673.16
Encroach Node=11155
       1 2559.69 2673.16
Encroach Node=11074
       1 2604.69 2718.16
Encroach Node=10707
       1 2622.99 2720.52
Encroach Node=10022
       1 2637.22 2736.43
Encroach Node=8814
       1 2651.47 2753.65
Encroach Node=8646
       1 2653.67 2753.57
Encroach Node=8551
       1  2629.7 2750.57
Encroach Node=8528
       1  2629.7 2754.57
Encroach Node=8505
       1 2654.67 2754.57
Encroach Node=8447
       1 2641.67 2741.57
Encroach Node=8293
       1 2645.58 2738.64
Encroach Node=7390
       1 2579.26 2682.74
Encroach Node=7139
       1 2579.26 2682.74
Encroach Node=7019
       1 2577.34 2681.46
Encroach Node=7014
       1 2577.34 2681.46
Encroach Node=7009
       1 2578.84 2681.46
Encroach Node=6889
       1 2594.34 2696.96
Encroach Node=6841
       1 2601.34 2703.96
Encroach Node=6155
       1 2713.97 2824.41
Encroach Node=5294
       1 2711.62 2826.84
Encroach Node=4773
       1 2732.13 2849.46
Encroach Node=4693
       1 2741.13 2858.46
Encroach Node=4586
       1 2736.66 2882.19
Encroach Node=4554
       1 2736.66 2882.19
Encroach Node=4522
       1 2738.16 2882.19
Encroach Node=4424
       1 2741.25 2885.69
Encroach Node=4331
       1 2736.97 2911.22
Encroach Node=3499
       1  2763.6 2920.11
Encroach Node=3411
       1  2756.6 2913.11
Encroach Node=3279
       1 2732.09 2886.03
Encroach Node=3231
       1 2732.09 2886.03
Encroach Node=3182
       1 2732.09 2871.03
Encroach Node=3068
       1 2723.34 2873.97
Encroach Node=2755
       1 2728.97 2885.79
Encroach Node=2036
       1 2707.64 2884.48
Encroach Node=1197
       1 2904.03 3079.82
Encroach Node=514
       1 3204.72 3334.71
Encroach Node=369
       1 3235.72 3365.71
Encroach Node=275
       1 3201.19 3417.88
Encroach Node=265
       1 3201.19 3417.88
Encroach Node=255
       1 3223.19 3417.88
Encroach Node=183
       1 3184.19 3378.88
Encroach Node=84
       1 3136.19 3330.88
Computation Interval=1HOUR
Output Interval=1HOUR
Run HTab= 0
Run UNet= 0
Run PostProcess= 0
UNET Theta= 1
UNET ZTol= 0.02
UNET ZSATol= 0.1
UNET MxIter= 20
UNET MaxInSteps= 20
UNET DtIC= 0
UNET DtMin= 0
UNET MaxCRTS= 20
UNET WFStab= 2
UNET SFStab= 1
UNET WFX= 1
UNET SFX= 1
UNET Convert EG Bridges=-1
UNET Use Existing IB Tables=-1
Instantaneous Interval=1HOUR
Write IC File= 0
Write Velocity= 0
Write Detailed= 0

--- D122-00-00.p02 (plan) ---

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Plan Title=FEMA Effective June 2007
Short Identifier=FEMAeff0607
Geom File=g04
Flow File=f02
Encroach Param=-1 ,0,0, 0

--- D122-00-00.p05 (plan) ---

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Plan Title=Storage Routing
Short Identifier=Store_Rout
Geom File=g04
Flow File=f04
Encroach Param=-1 ,0,0, 0

--- D122-00-00.f05 (steady flow) ---

Flow Title=Floodway
Version=Version 3.0.1  Mar 2001
Number of Profiles= 2
Profile Names=1PCT_100yr,1PCTFloodway_100yrFW
River Rch & RM=D122-00-00,D122-00-00_0001 ,17298
    1323    1323
River Rch & RM=D122-00-00,D122-00-00_0001 ,16831
    1487    1487
River Rch & RM=D122-00-00,D122-00-00_0001 ,16054
    1737    1737
River Rch & RM=D122-00-00,D122-00-00_0001 ,15023
    1982    1982
River Rch & RM=D122-00-00,D122-00-00_0001 ,14145
    2178    2178
River Rch & RM=D122-00-00,D122-00-00_0001 ,13520
    2521    2521
River Rch & RM=D122-00-00,D122-00-00_0001 ,12550
    2743    2743
River Rch & RM=D122-00-00,D122-00-00_0001 ,11989
    3148    3148
River Rch & RM=D122-00-00,D122-00-00_0001 ,11074
    3373    3373
River Rch & RM=D122-00-00,D122-00-00_0001 ,10022
    3778    3778
River Rch & RM=D122-00-00,D122-00-00_0001 ,8293
    4155    4155
River Rch & RM=D122-00-00,D122-00-00_0001 ,6841
    4599    4599
River Rch & RM=D122-00-00,D122-00-00_0001 ,5294
    4899    4899
River Rch & RM=D122-00-00,D122-00-00_0001 ,4331
    5322    5322
River Rch & RM=D122-00-00,D122-00-00_0001 ,3068
    5694    5694
River Rch & RM=D122-00-00,D122-00-00_0001 ,2036
    6016    6016
River Rch & RM=D122-00-00,D122-00-00_0001 ,1197
    6507    6507
Boundary for River Rch & Prof#=D122-00-00,D122-00-00_0001 , 1
Up Type= 0
Dn Type= 1
Dn Known WS=65.01
Boundary for River Rch & Prof#=D122-00-00,D122-00-00_0001 , 2
Up Type= 0
Dn Type= 1
Dn Known WS=65.01
DSS Import GetInterval= 0
DSS Import GetPeak= 0
DSS Import FillOption= 0

--- D122-00-00.f02 (steady flow) ---

Flow Title=FEMA Effective June 2007
Version=Version 3.0.1  Mar 2001
Number of Profiles= 4
Profile Names=10PCT_10yr,2PCT_50yr,1PCT_100yr,0.2PCT_500yr
River Rch & RM=D122-00-00,D122-00-00_0001 ,17298
     790    1143    1323    1817
River Rch & RM=D122-00-00,D122-00-00_0001 ,16831
     871    1280    1487    2060
River Rch & RM=D122-00-00,D122-00-00_0001 ,16054
     992    1486    1737    2431
River Rch & RM=D122-00-00,D122-00-00_0001 ,15023
    1108    1689    1982    2800
River Rch & RM=D122-00-00,D122-00-00_0001 ,14145
    1198    1849    2178    3096
River Rch & RM=D122-00-00,D122-00-00_0001 ,13520
    1354    2129    2521    3618
River Rch & RM=D122-00-00,D122-00-00_0001 ,12550
    1453    2310    2743    3959
River Rch & RM=D122-00-00,D122-00-00_0001 ,11989
    1630    2638    3148    4587
River Rch & RM=D122-00-00,D122-00-00_0001 ,11074
    1739    2839    3373    4868
River Rch & RM=D122-00-00,D122-00-00_0001 ,10022
    1935    3204    3778    5368
River Rch & RM=D122-00-00,D122-00-00_0001 ,8293
    2115    3546    4155    5828
River Rch & RM=D122-00-00,D122-00-00_0001 ,6841
    2327    3952    4599    6361
River Rch & RM=D122-00-00,D122-00-00_0001 ,5294
    2469    4227    4899    6718
River Rch & RM=D122-00-00,D122-00-00_0001 ,4331
    2669    4617    5322    7215
River Rch & RM=D122-00-00,D122-00-00_0001 ,3068
    2844    4962    5694    7648
River Rch & RM=D122-00-00,D122-00-00_0001 ,2036
    2995    5262    6016    8020
River Rch & RM=D122-00-00,D122-00-00_0001 ,1197
    3224    5721    6507    8582
Boundary for River Rch & Prof#=D122-00-00,D122-00-00_0001 , 1
Up Type= 0
Dn Type= 3
Dn Slope=.001
Boundary for River Rch & Prof#=D122-00-00,D122-00-00_0001 , 2
Up Type= 0
Dn Type= 3
Dn Slope=.001
Boundary for River Rch & Prof#=D122-00-00,D122-00-00_0001 , 3
Up Type= 0
Dn Type= 3
Dn Slope=.001
Boundary for River Rch & Prof#=D122-00-00,D122-00-00_0001 , 4
Up Type= 0
Dn Type= 3
Dn Slope=.001
DSS Import GetInterval= 0
DSS Import GetPeak= 0
DSS Import FillOption= 0

--- D122-00-00.f04 (steady flow) ---

Flow Title=Storage Routing
Version=Version 3.0.1  Mar 2001
Number of Profiles= 8
Profile Names=0.1,0.2,0.4,0.6,0.8,1.0,1.2,1.5
River Rch & RM=D122-00-00,D122-00-00_0001 ,17298
     315     630    1260    1890    2520    3150    3780    4725
River Rch & RM=D122-00-00,D122-00-00_0001 ,11074
     650    1300    2600    3900    5200    6500    7800    9750
Boundary for River Rch & Prof#=D122-00-00,D122-00-00_0001 , 1
Up Type= 0
Dn Type= 3
Dn Slope=.001
Boundary for River Rch & Prof#=D122-00-00,D122-00-00_0001 , 2
Up Type= 0
Dn Type= 3
Dn Slope=.001
Boundary for River Rch & Prof#=D122-00-00,D122-00-00_0001 , 3
Up Type= 0
Dn Type= 3
Dn Slope=.001
Boundary for River Rch & Prof#=D122-00-00,D122-00-00_0001 , 4
Up Type= 0
Dn Type= 3
Dn Slope=.001
Boundary for River Rch & Prof#=D122-00-00,D122-00-00_0001 , 5
Up Type= 0
Dn Type= 3
Dn Slope=.001
Boundary for River Rch & Prof#=D122-00-00,D122-00-00_0001 , 6
Up Type= 0
Dn Type= 3
Dn Slope=.001
Boundary for River Rch & Prof#=D122-00-00,D122-00-00_0001 , 7
Up Type= 0
Dn Type= 3
Dn Slope=.001
Boundary for River Rch & Prof#=D122-00-00,D122-00-00_0001 , 8
Up Type= 0
Dn Type= 3
Dn Slope=.001
DSS Import GetInterval= 0
DSS Import GetPeak= 0
DSS Import FillOption= 0

--- D122-00-00.g04 (geometry) ---

Geom Title=D122-00-00 June 2007
Version=Version 3.0.1  Mar 2001

River Reach=D122-00-00      ,D122-00-00_0001
Reach XY= 30
     3042500.588    13816175.231     3043198.022    13816196.496
     3047223.411    13816371.107     3047699.418    13816358.846
     3048809.188    13816405.074     3050546.963    13816435.836
     3051753.792     13816472.34     3052002.576    13816507.276
     3052177.285    13816549.437      3052371.13    13816577.855
     3053238.148    13816615.235     3053341.626    13816609.527
     3053565.368    13816558.468     3053752.357    13816505.511
     3053985.419    13816488.077     3054444.078    13816526.479
     3054900.009    13816546.325     3055544.141    13816561.154
     3055640.268    13816555.067     3055746.474    13816567.913
     3056331.423    13816587.052      3056878.86    13816618.987
     3057393.431    13816630.811     3057783.019    13816650.916
     3057834.285    13816657.245     3057992.399    13816735.377
     3058128.008    13816749.741     3059987.101    13816786.758
     3060081.523    13816813.727      3060140.59    13816859.768

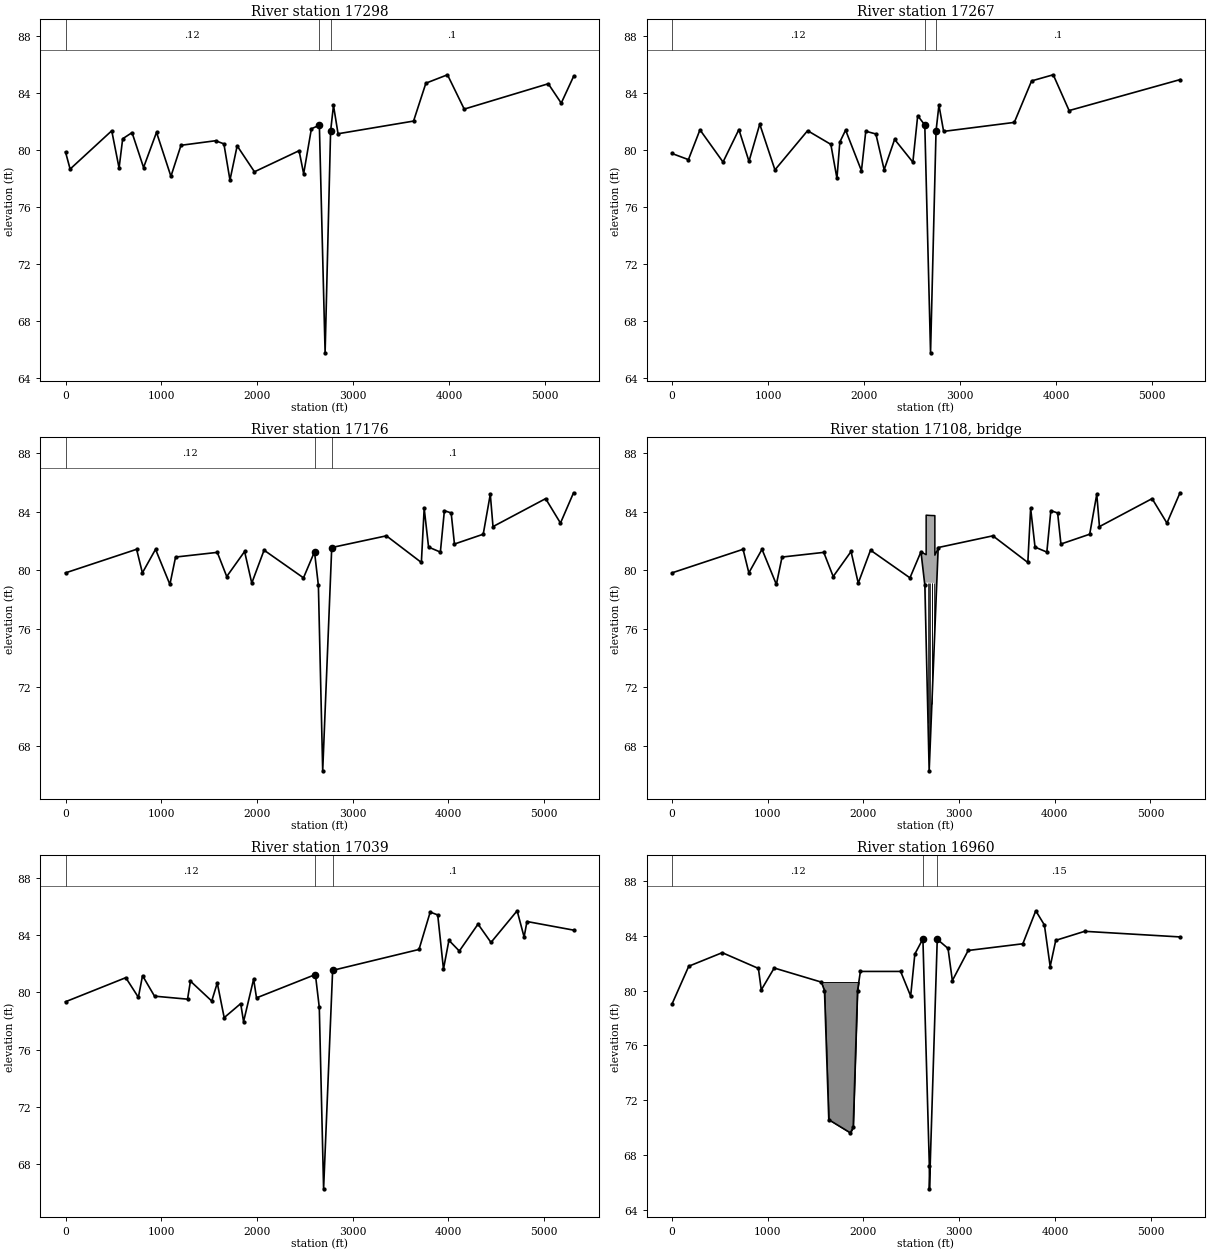
Type RM Length L Ch R = 1 ,17298   ,62.75,31.23,16.21
BEGIN DESCRIPTION:
17298.67
END DESCRIPTION:
XS GIS Cut Line= 5
     3042703.525    13818880.574     3042832.404    13816441.203
     3042907.362    13816250.111     3042932.767       13816105.
     3043061.989    13813604.236
#Sta/Elev= 30
       0   79.87   48.14   78.67  482.28   81.36  558.85   78.74  596.41    80.8
  694.04   81.23  814.21   78.78   949.4   81.25 1099.61   78.16 1204.75   80.34
 1565.25   80.66 1652.18   80.44 1715.46    77.9 1790.57    80.3 1970.82   78.48
 2436.47   79.96 2484.11   78.34 2564.91    81.5 2648.04   81.75 2707.94   65.77
 2765.17   81.33 2795.36   83.14 2842.92   81.15  3630.6   82.04  3759.1    84.7
 3984.44   85.29 4159.04   82.88 5035.84   84.66 5171.02    83.3 5299.46   85.17
#Mann= 3 , 0 , 0
       0     .12       0 2648.04     .04       0 2765.17      .1       0
#XS Ineff= 2 , 0
       0    2640            2836       0
Permanent Ineff=
       T       T
Bank Sta=2648.04,2765.17
XS Rating Curve= 0
Exp/Cntr=.3,.1

Type RM Length L Ch R = 1 ,17267   ,92.24,91.21,91.52
BEGIN DESCRIPTION:
17267.44
END DESCRIPTION:
XS GIS Cut Line= 5
     3042805.569    13818883.668     3042938.468    13816454.323
     3042949.006      13816261.7     3042949.006    13816097.146
      3043098.34    13813599.045
#Sta/Elev= 30
       0   79.75  171.42   79.32   291.6   81.41  531.96   79.15  697.21   81.43
  802.37    79.2  914.51   81.81 1072.77    78.6 1413.02   81.35 1655.16   80.39
 1718.73   78.01 1748.78   80.55 1808.87   81.39 1974.12   78.54 2019.18   81.31
 2124.34   81.12 2210.65   78.61 2319.63   80.74 2509.75   79.14 2559.99    82.4
 2634.04   81.75 2693.94   65.77 2751.17   81.33 2781.36   83.14 2830.16    81.3
 3566.47   81.93 3746.79   84.84 3972.19   85.27 4137.49   82.76    5293   84.93
#Mann= 3 , 0 , 0
       0     .12       0 2634.04     .04       0 2751.17      .1       0
#XS Ineff= 2 , 0
       0    2630            2823       0
Permanent Ineff=
       T       T
Bank Sta=2634.04,2751.17
XS Rating Curve= 0
Exp/Cntr=.5,.3

Type RM Length L Ch R = 1 ,17176   ,136.3,137.14,138.67
BEGIN DESCRIPTION:
17176.23
END DESCRIPTION:
XS GIS Cut Line= 4
     3042938.727    13818887.706     3043040.162    13816269.953
     3043040.206    13816099.895     3043205.916     13813585.57
#Sta/Elev= 30
       0   79.81  743.11   81.42  803.47   79.81  940.91   81.42 1091.02   79.02
  1150.3   80.89  1586.4   81.21    1685   79.56 1871.61   81.27 1946.67   79.11
 2075.18   81.36 2487.07   79.47 2602.28   81.25 2642.93   78.95 2687.94   66.29
  2782.3   81.54  3353.6   82.34 3719.18   80.52 3748.49   84.22 3794.34   81.57
 3917.73   81.23  3959.7   84.06 4030.55    83.9 4064.93   81.78 4365.58   82.45
 4439.54   85.18 4467.75   82.97 5017.77   84.88  5172.9   83.21 5309.56   85.28
#Mann= 3 , 0 , 0
       0     .12       0 2602.28    .015       0  2782.3      .1       0
#XS Ineff= 2 , 0
       0    2600            2811       0
Permanent Ineff=
       T       T
Bank Sta=2602.28,2782.3
XS Rating Curve= 0
Exp/Cntr=.5,.3

Type RM Length L Ch R = 3 ,17108   ,,,
BEGIN DESCRIPTION:
Synott Bridge and Crosswalk
END DESCRIPTION:
Bridge Culvert--1,0,-1,-1, 0
Deck Dist Width WeirC Skew NumUp NumDn MinLoCord MaxHiCord MaxSubmerge Is_Ogee
5,115,2.6,0, 7, 7, , , .95, 0, 0,0,,
    2602 2656.38 2656.38 2701.98 2747.58 2747.58 2782.29
   81.25   81.05   83.75   83.73   83.72   81.02   81.49
       0       0   79.15   79.13   79.12       0       0
    2611 2665.39 2665.39 2710.99 2756.59 2756.59  2791.3
   81.23   81.05   83.75   83.73   83.72   81.02   81.54
       0       0   79.15   79.13   79.12       0       0
Pier Skew, UpSta & Num, DnSta & Num=  ,2676.38, 2 ,2685.39, 2 , 0 , 0 , 0 ,,
       1       1
     -.4    79.6
       1       1
     -.4    79.6
Pier Skew, UpSta & Num, DnSta & Num=  ,2686.38, 2 ,2695.39, 2 , 0 , 0 , 0 ,,
    1.35    1.35
       0   79.55
    1.35    1.35
       0   79.55
Pier Skew, UpSta & Num, DnSta & Num=  ,2699.38, 2 ,2708.39, 2 , 0 , 0 , 0 ,,
       1       1
       0      80
       1       1
       0      80
Pier Skew, UpSta & Num, DnSta & Num=  ,2716.38, 2 ,2725.39, 2 , 0 , 0 , 0 ,,
    1.35    1.35
       0   79.55
    1.35    1.35
       0   79.55
Pier Skew, UpSta & Num, DnSta & Num=  ,2720.38, 2 ,2729.39, 2 , 0 , 0 , 0 ,,
       1       1
       0      80
       1       1
       0      80
Pier Skew, UpSta & Num, DnSta & Num=  ,2740.38, 2 ,2749.39, 2 , 0 , 0 , 0 ,,
       1       1
       0      80
       1       1
       0      80
BR Coef=-1 , 1 , 1 ,1.25, 0 ,,,.8,-1,2,0,
WSPro=,,,, 1 ,,,, 0 ,,,, 0 ,,,,-1 ,-1 ,-1 , 0 , 0 , 0 , 0 , 0
BC Design=,, 0 ,, 0 ,,,,,,

Type RM Length L Ch R = 1 ,17039   ,80.51,79.16,77.3
BEGIN DESCRIPTION:
17039.09
END DESCRIPTION:
XS GIS Cut Line= 4
     3043077.122    13818891.903     3043176.428    13816272.435
     3043178.366     13816103.92     3043369.843    13813592.291
#Sta/Elev= 30
       0   79.35  629.85   81.03  761.48   79.66  804.87   81.17  930.07   79.74
 1275.32   79.53 1305.34   80.79 1527.99    79.4 1585.84   80.66 1658.15   78.24
 1830.72   79.22 1860.63   77.96 1965.81   80.93 1995.84   79.62 2611.28   81.25
 2651.93   78.95 2696.94   66.29  2791.3   81.54 3693.91      83 3810.78   85.61
 3889.48   85.41 3949.65   81.63 4006.47   83.64 4115.13   82.89  4310.7   84.77
 4446.09   83.49 4719.35    85.7 4792.09   83.87 4822.18   84.95  5308.8   84.35
#Mann= 3 , 0 , 0
       0     .12       0 2611.28    .015       0  2791.3      .1       0
#XS Ineff= 2 , 0
       0    2600            2800       0
Permanent Ineff=
       T       T
Bank Sta=2611.28,2791.3
XS Rating Curve= 0
Exp/Cntr=.5,.3

Type RM Length L Ch R = 1 ,16960   ,128.11,128.36,127.37
BEGIN DESCRIPTION:
16959.93
END DESCRIPTION:
XS GIS Cut Line= 4
     3043179.762    13818895.016     3043256.406    13816276.627
     3043256.406     13816106.41     3043406.743    13813593.474
#Sta/Elev= 30
       0   79.02   175.2   81.79  525.11   82.78   902.9   81.63  932.92   80.06
 1067.97   81.66 1560.27   80.63  1593.2   80.01 1638.22   70.58 1863.31   69.62
 1893.33   70.02 1938.35   80.01 1968.36   81.41 2388.54   81.41 2493.37   79.61
 2537.11   82.68 2621.32   83.79 2688.63   67.21 2689.68   65.53 2771.17   83.76
 2883.81   83.09 2928.89   80.74 3094.18   82.94  3665.2   83.43 3800.44   85.84
  3890.6    84.8 3950.71   81.77 4009.09   83.68 4311.35   84.34 5307.16   83.93
#Mann= 3 , 0 , 0
       0     .12       0 2621.32     .04       0 2771.17     .15       0
#XS Ineff= 2 , 0
       0    2615            2780       0
Permanent Ineff=
       T       T
#Block Obstruct= 1 ,-1
 1559.99 2020.91   80.64
Bank Sta=2621.32,2771.17
XS Rating Curve= 0
Exp/Cntr=.3,.1

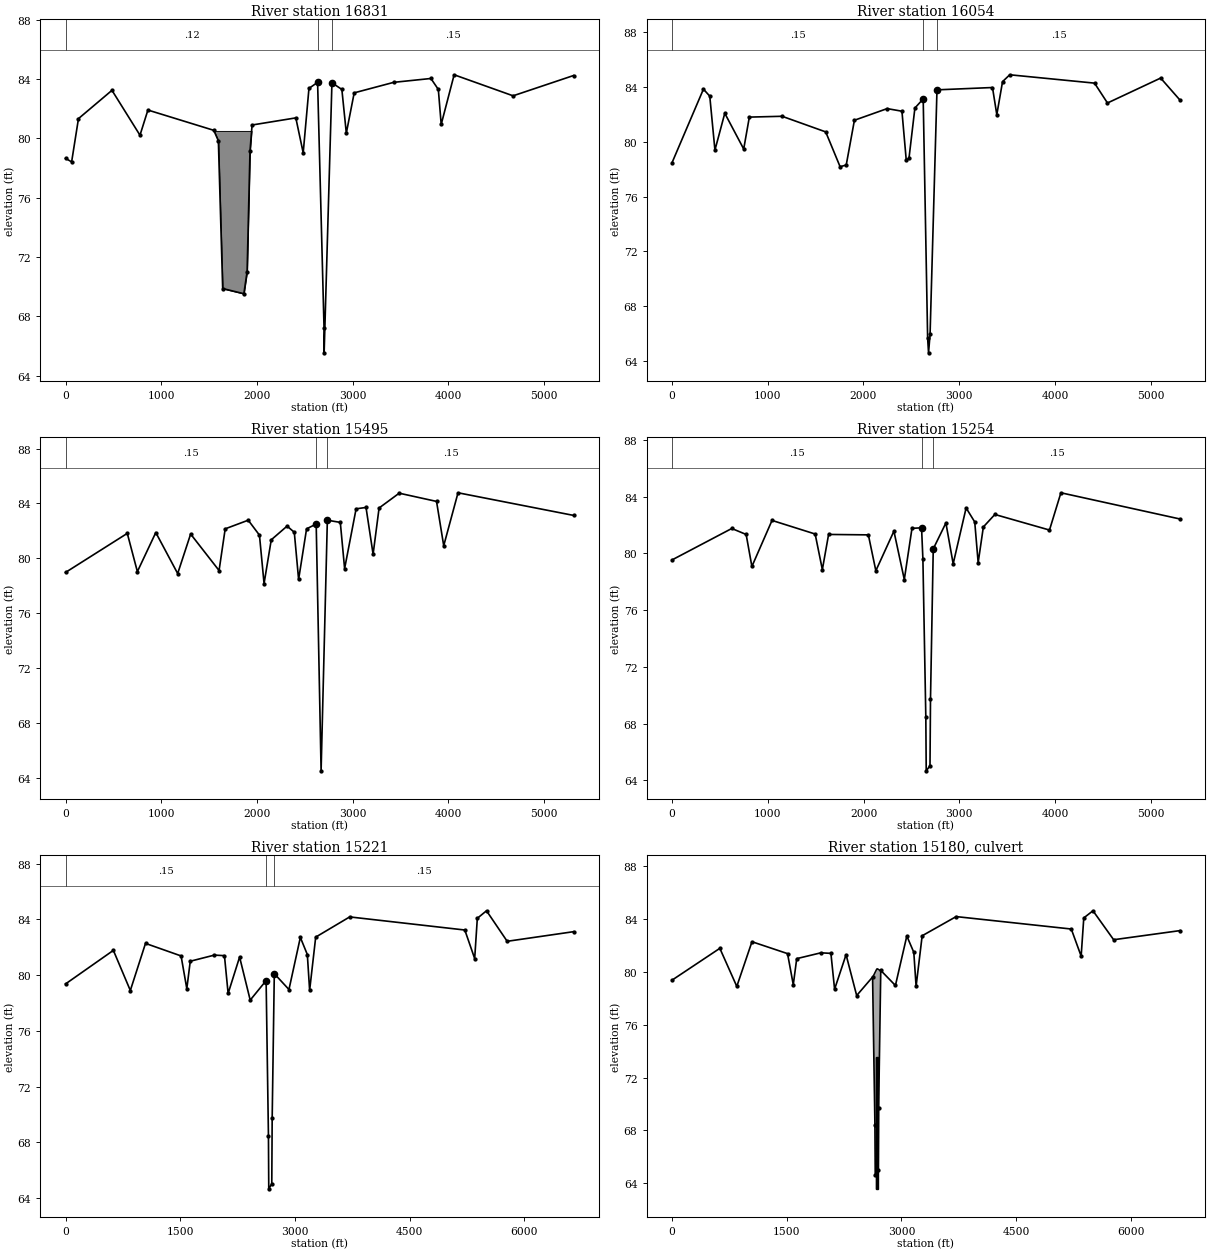
Type RM Length L Ch R = 1 ,16831   ,776.29,777.3,777.42
BEGIN DESCRIPTION:
16831.57
END DESCRIPTION:
XS GIS Cut Line= 4
     3043249.943    13818897.144     3043385.521    13816282.134
     3043383.671     13816121.23     3043508.628    13813596.739
#Sta/Elev= 30
       0   78.66   63.97   78.42  135.37   81.34  485.29   83.25  777.96   80.22
   860.8   81.92 1549.07   80.55 1596.79   79.84 1641.85   69.87 1863.23   69.52
 1897.19   71.02 1927.23   79.13 1948.91   80.91 2405.86   81.39 2482.97   79.03
 2543.05   83.38 2633.32   83.79 2700.63   67.21 2701.68   65.53 2783.17   83.76
 2886.82   83.31 2933.35   80.36 3015.61   83.08 3428.96   83.79 3816.97   84.05
 3894.53   83.31 3924.56   80.95 4059.73    84.3 4675.48   82.88 5307.01   84.25
#Mann= 3 , 0 , 0
       0     .12       0 2633.32     .04       0 2783.17     .15       0
#XS Ineff= 2 , 0
       0    2622            2790       0
Permanent Ineff=
       T       T
#Block Obstruct= 1 ,-1
 1549.01 1994.75   80.51
Bank Sta=2633.32,2783.17
XS Rating Curve= 0
Exp/Cntr=.3,.1

Type RM Length L Ch R = 1 ,16054   ,559.02,558.82,556.73
BEGIN DESCRIPTION:
16054.26
END DESCRIPTION:
XS GIS Cut Line= 4
     3044020.007    13818920.496     3044161.137    13816316.593
     3044161.137    13816156.882     3044247.395    13813620.418
#Sta/Elev= 30
       0   78.46  328.48   83.84  394.71   83.33  448.65   79.39  551.45   82.08
  749.09   79.47  807.95    81.8 1149.94   81.86 1605.35   80.72 1755.57   78.18
 1819.67    78.3 1905.17   81.57 2247.16   82.42 2401.52   82.23 2446.58   78.65
 2475.16    78.8 2536.71   82.46 2623.47   83.13 2669.83   65.66 2679.35   64.59
 2695.22   65.94 2767.44   83.79 3347.15   83.96 3392.18   81.98 3452.21   84.39
 3527.26   84.89 4412.77   84.28 4547.85   82.83 5103.17   84.65 5305.37   83.04
#Mann= 3 , 0 , 0
       0     .15       0 2623.47     .04       0 2767.44     .15       0
#XS Ineff= 2 , 0
       0    2608            2797       0
Permanent Ineff=
       T       T
Bank Sta=2623.47,2767.44
XS Rating Curve= 0
Exp/Cntr=.3,.1

Type RM Length L Ch R = 1 ,15495   ,242.1,241.34,243.3
BEGIN DESCRIPTION:
15495.44
END DESCRIPTION:
XS GIS Cut Line= 4
      3044540.31    13818936.274     3044720.269    13816341.752
     3044718.369    13816178.454     3044756.056    13813636.722
#Sta/Elev= 30
       0   78.97  645.32   81.82  750.57   79.03  942.98   81.88 1171.58   78.89
 1306.91   81.77 1603.83   79.11 1667.77   82.15 1908.35   82.78 2025.65   81.69
 2073.74   78.16 2148.93   81.35 2314.32   82.35  2389.5    81.9 2434.61   78.46
 2517.78   82.15 2618.21    82.5 2669.45    64.5 2734.77   82.78 2870.03   82.62
 2915.04   79.25 3035.05   83.61 3138.64   83.71 3212.55    80.3 3275.08   83.67
  3485.1   84.75 3875.14   84.15 3950.15   80.92  4099.5   84.78 5306.08   83.13
#Mann= 3 , 0 , 0
       0     .15       0 2618.21     .04       0 2734.77     .15       0
#XS Ineff= 2 , 0
       0    2601            2742       0
Permanent Ineff=
       T       T
Bank Sta=2618.21,2734.77
XS Rating Curve= 0
Exp/Cntr=.3,.1

Type RM Length L Ch R = 1 ,15254   ,33.16,32.73,34.19
BEGIN DESCRIPTION:
15254.11
END DESCRIPTION:
XS GIS Cut Line= 4
     3044870.795    13818946.296      3044960.47    13816354.416
      3044960.47    13816206.187     3045024.098    13813645.313
#Sta/Elev= 30
       0   79.54  624.17   81.76  774.26   81.34  834.29   79.08 1044.42   82.33
 1494.69   81.37 1569.73   78.86 1634.95   81.34 2050.02   81.31 2128.19   78.78
 2316.78   81.57 2425.25   78.16 2505.37   81.77 2605.35   81.81 2619.38    79.6
  2649.9   68.44 2654.03   64.66 2693.47   65.02 2698.68   69.73 2727.38   80.32
 2859.49   82.15 2935.41   79.27 3070.45   83.21 3160.48   82.22 3196.23   79.35
  3250.5   81.87 3370.54   82.75 3940.72   81.65 4060.04   84.28 5303.32   82.43
#Mann= 3 , 0 , 0
       0     .15       0 2605.35     .04       0 2727.38     .15       0
#XS Ineff= 2 , 0
       0    2597            2730       0
Permanent Ineff=
       T       T
Bank Sta=2605.35,2727.38
XS Rating Curve= 0
Exp/Cntr=.5,.3

Type RM Length L Ch R = 1 ,15221   ,81.62,81.68,82.65
BEGIN DESCRIPTION:
15221.38
END DESCRIPTION:
XS GIS Cut Line= 4
     3044930.221    13818948.099      3044993.17    13816354.937
      3044993.17    13816206.709     3045178.227    13812310.739
#Sta/Elev= 30
       0   79.36  625.78   81.77  847.56   78.89 1045.91   82.27 1511.04   81.37
 1586.07   79.02 1631.08   80.99 1946.17   81.43 2078.06   81.39 2126.22   78.68
 2276.27   81.29 2414.98    78.2 2622.88    79.6  2653.4   68.44 2657.53   64.66
 2696.97   65.02 2702.18   69.73 2729.94    80.1 2921.56   78.96 3070.48    82.7
 3161.84   81.47 3191.87    78.9 3271.19   82.72  3715.6   84.17 5220.88   83.23
  5349.9   81.18 5384.34   84.07 5504.47   84.61 5774.78   82.42 6642.52   83.11
#Mann= 3 , 0 , 0
       0     .15       0 2622.88    .015       0 2729.94     .15       0
#XS Ineff= 2 , 0
       0    2596            2740       0
Permanent Ineff=
       T       T
Bank Sta=2622.88,2729.94
XS Rating Curve= 0
Exp/Cntr=.5,.3

Type RM Length L Ch R = 2 ,15180   ,,,
BEGIN DESCRIPTION:
Timberway Bridge
END DESCRIPTION:
Bridge Culvert--1,0,-1,-1, 0
Deck Dist Width WeirC Skew NumUp NumDn MinLoCord MaxHiCord MaxSubmerge Is_Ogee
5,40,2.6,0, 4, 5, , , .95, 0, 0,0,,
 2622.89 2677.71 2687.77 2729.94
   79.57   80.21   80.22   80.06
     -.4     -.4     -.4     -.4
 2612.89 2667.71 2677.77 2720.06 2720.06
    79.6   80.21   80.22   80.14   80.11
     -.4     -.4     -.4     -.4     -.4
BR Coef=-1 , 1 , 1 ,1.25, 0 ,,,.8,-1,2,0,
WSPro=,,,, 1 ,,,, 0 ,,,, 0 ,,,,-1 ,-1 ,-1 , 0 , 0 , 0 , 0 , 0
Multiple Barrel Culv=2,10,10,40,.015,.5,.1,8,1,63.58,63.58, 3,Culvert #1  , 0 ,5
 2667.21 2657.21 2677.71 2667.71 2688.21 2678.21
Culvert Bottom n=.015
BC Design=,, 0 ,, 0 ,,,,,,

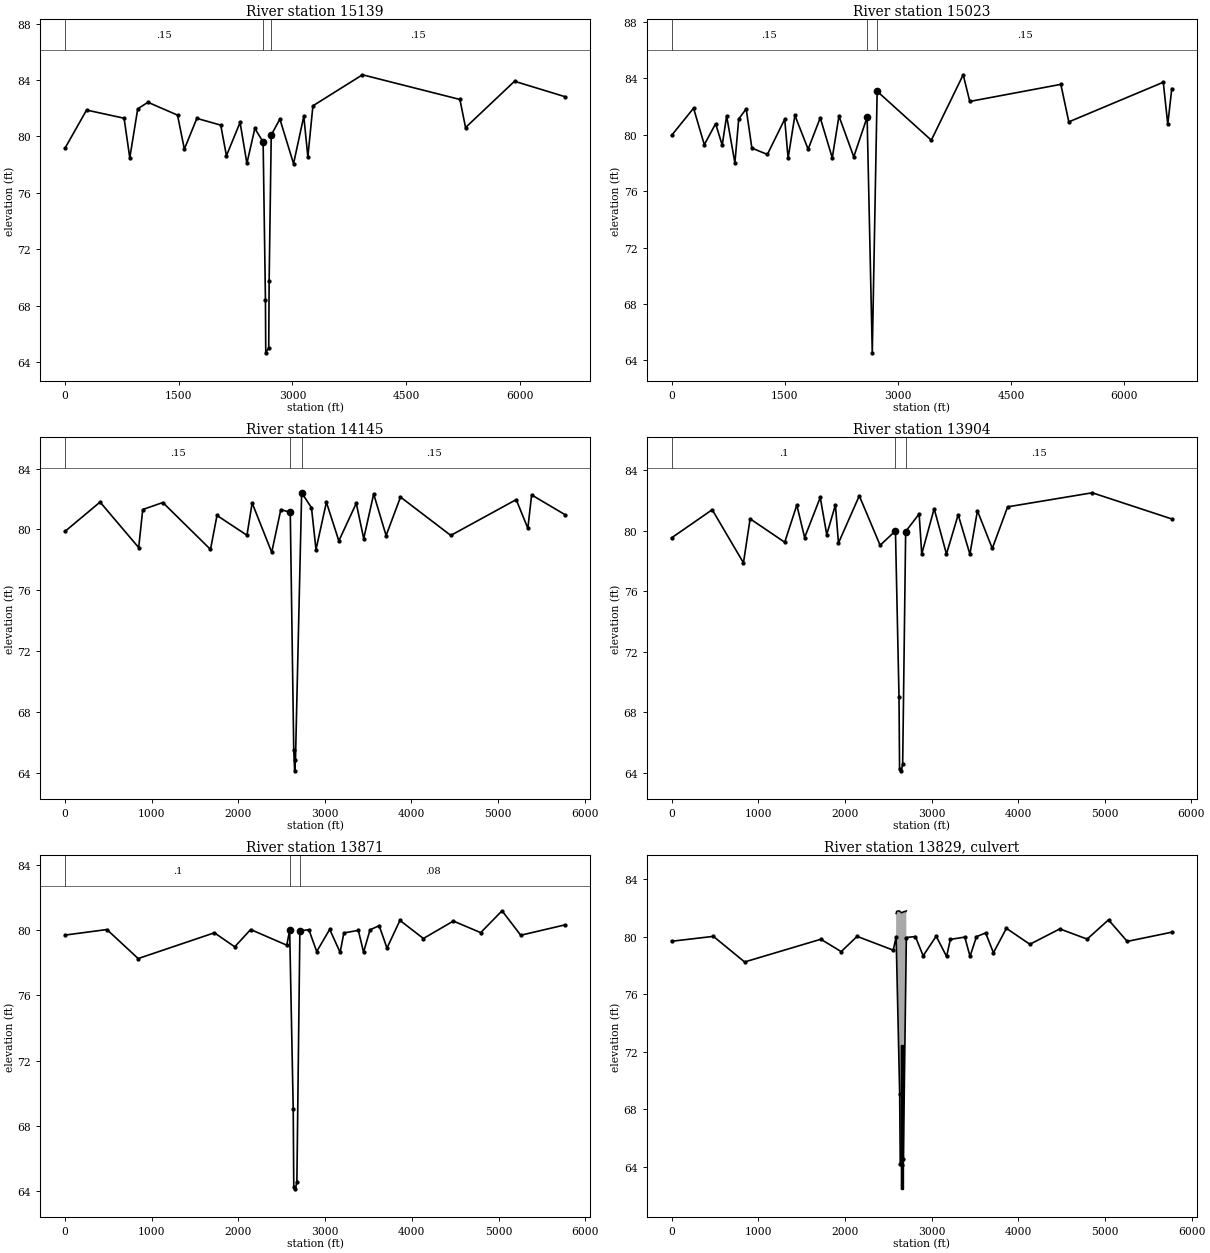
Type RM Length L Ch R = 1 ,15139   ,108.51,116.19,126.02
BEGIN DESCRIPTION:
15139.70
END DESCRIPTION:
XS GIS Cut Line= 4
     3045010.138    13818950.522     3045074.778    13816357.013
     3045074.778    13816208.785     3045320.335    13812358.505
#Sta/Elev= 30
       0   79.18  283.11   81.87  778.26   81.29  853.29   78.48  958.32   81.96
 1093.36   82.42 1483.48   81.51 1573.51    79.1 1738.56   81.28 2053.66    80.8
 2128.68   78.63 2308.74   80.99 2398.77   78.09  2503.8   80.57 2612.88    79.6
  2643.4   68.44 2647.53   64.66 2686.97   65.02 2692.18   69.73 2719.94    80.1
 2834.01   81.23 3014.38   78.07 3149.65   81.43 3203.16   78.55  3269.9   82.17
 3923.76   84.37 5209.54   82.62 5283.99   80.63 5930.14   83.91 6600.65   82.81
#Mann= 3 , 0 , 0
       0     .15       0 2612.88    .015       0 2719.94     .15       0
#XS Ineff= 2 , 0
       0    2594            2727       0
Permanent Ineff=
       T       T
Bank Sta=2612.88,2719.94
XS Rating Curve= 0
Exp/Cntr=.5,.3

Type RM Length L Ch R = 1 ,15023   ,876.6,878.06,873.44
BEGIN DESCRIPTION:
15023.50
END DESCRIPTION:
XS GIS Cut Line= 4
     3045111.666    13818936.197      3045183.29    13816362.879
     3045198.063    13816213.373     3045614.109    13812330.358
#Sta/Elev= 30
       0   79.95  291.53   81.88  433.86   79.29  583.52   80.78  671.12   79.26
  729.52   81.33  839.02      78  890.11   81.12  989.08   81.83 1064.11   79.05
  1269.7    78.6 1499.28    81.1  1544.3   78.33 1634.33   81.37 1809.88   78.97
 1970.47    81.2 2129.52   78.36 2218.66   81.32 2414.63   78.43 2591.64   81.24
 2660.07   64.53 2724.55   83.08 3442.46   79.61 3864.86   84.25 3952.41   82.36
 5159.28   83.57 5264.88   80.91 6517.01   83.72 6576.42   80.74 6629.79   83.27
#Mann= 3 , 0 , 0
       0     .15       0 2591.64     .04       0 2724.55     .15       0
#XS Ineff= 2 , 0
       0    2570            2730       0
Permanent Ineff=
       T       T
Bank Sta=2591.64,2724.55
XS Rating Curve= 0
Exp/Cntr=.3,.1

Type RM Length L Ch R = 1 ,14145   ,249.63,240.96,232.23
BEGIN DESCRIPTION:
14145.44
END DESCRIPTION:
XS GIS Cut Line= 4
     3045856.745    13818976.196     3046061.249    13816401.498
     3046074.428    13816252.824     3046212.071    13813210.755
#Sta/Elev= 30
       0   79.88  403.75    81.8  849.83   78.81  896.51   81.31 1128.63   81.77
 1678.97   78.69  1754.2   80.92 2100.29   79.62 2160.19   81.74 2386.19    78.5
 2491.52   81.31 2600.43   81.12 2640.57   65.54 2651.24   64.15 2660.57   64.88
 2732.06   82.41 2845.45   81.43 2897.56   78.68 3017.68   81.79 3161.49   79.25
  3362.6   81.72  3448.8    79.4 3563.72   82.33 3707.37    79.6 3873.55   82.13
 4454.37   79.61 5209.92   81.96 5344.26   80.08 5388.12   82.27 5777.25   80.96
#Mann= 3 , 0 , 0
       0     .15       0 2600.43     .04       0 2732.06     .15       0
#XS Ineff= 2 , 0
       0    2586            2740       0
Permanent Ineff=
       T       T
Bank Sta=2600.43,2732.06
XS Rating Curve= 0
Exp/Cntr=.3,.1

Type RM Length L Ch R = 1 ,13904   ,33.13,33.06,33.09
BEGIN DESCRIPTION:
13904.48
END DESCRIPTION:
XS GIS Cut Line= 6
     3046172.505    13818985.771     3046307.681     13816447.04
     3046309.585    13816260.511     3046309.019    13816236.062
     3046309.019    13816159.212     3046462.596     13813220.72
#Sta/Elev= 30
       0   79.54  468.93    81.4  829.44   77.89  906.36    80.8 1305.69   79.25
 1445.32   81.71 1535.44   79.56  1715.7   82.21 1790.59   79.76 1890.43   81.71
    1926    79.2 2166.34   82.32 2406.68   79.05 2583.59      80 2624.57   69.05
    2631   64.23 2649.93   64.14 2666.86   64.57 2701.44   79.96 2856.92   81.12
 2886.96   78.47  3030.2   81.47 3172.35   78.47 3307.53   81.07 3442.72   78.46
  3529.8   81.33  3701.1   78.84 3878.31   81.59 4854.64   82.52 5772.67   80.79
#Mann= 3 , 0 , 0
       0      .1       0 2583.59     .04       0 2701.44     .15       0
#XS Ineff= 2 , 0
       0    2570            2710       0
Permanent Ineff=
       T       T
Bank Sta=2583.59,2701.44
XS Rating Curve= 0
Exp/Cntr=.5,.3

Type RM Length L Ch R = 1 ,13871   ,83.78,83.7,83.76
BEGIN DESCRIPTION:
13871.42
END DESCRIPTION:
XS GIS Cut Line= 6
     3046236.017    13818987.697     3046340.731     13816447.48
     3046342.635    13816260.951     3046342.069    13816236.502
     3046342.069    13816159.652      3046473.91    13813221.981
#Sta/Elev= 30
       0    79.7  482.23   80.04  842.69   78.26 1722.21   79.84 1956.86   78.98
 2140.34   80.04 2557.35   79.08 2590.59      80 2631.57   69.05    2638   64.23
 2656.93   64.14 2673.86   64.57 2708.44   79.96 2812.37   80.03 2902.44   78.69
 3052.59   80.05 3172.72   78.64  3215.9   79.83 3382.93   79.99 3442.99   78.65
 3517.67   80.02 3623.17   80.28 3713.26    78.9 3862.56    80.6 4133.68   79.49
 4479.03   80.56 4794.35   79.85 5040.91   81.19 5256.46   79.69 5770.85   80.33
#Mann= 3 , 0 , 0
       0      .1       0 2590.59    .015       0 2708.44     .08       0
#XS Ineff= 2 , 0
       0    2563            2710       0
Permanent Ineff=
       T       T
Bank Sta=2590.59,2708.44
XS Rating Curve= 0
Exp/Cntr=.5,.3

Type RM Length L Ch R = 2 ,13829   ,,,
BEGIN DESCRIPTION:
Dairy-Ashford Bridge
END DESCRIPTION:
Bridge Culvert--1,0,-1,-1, 0
Deck Dist Width WeirC Skew NumUp NumDn MinLoCord MaxHiCord MaxSubmerge Is_Ogee
5,75,2.6,0, 8, 8, , , .95, 0, 0,0,,
  2590.6 2596.52 2624.09 2654.15 2662.57 2687.43 2699.19 2708.45
   81.63   81.78   81.82   81.68   81.71   81.78   81.75   81.82
       0       0       0       0       0       0       0       0
 2580.57 2585.82 2613.39 2643.45 2651.87 2676.73 2688.49 2698.44
   81.63   81.78   81.82   81.68   81.71   81.78   81.75   81.82
       0       0       0       0       0       0       0       0
BR Coef=-1 , 1 , 1 ,1.25, 0 ,,,.8,-1,2,0,
WSPro=,,,, 1 ,,,, 0 ,,,, 0 ,,,,-1 ,-1 ,-1 , 0 , 0 , 0 , 0 , 0
Multiple Barrel Culv=2,10,10,75,.015,.5,.1,8,1,62.48,62.48, 3,Culvert #1  , 0 ,5
 2646.07 2635.37 2656.51 2645.81 2667.07 2656.37
Culvert Bottom n=.015
BC Design=,, 0 ,, 0 ,,,,,,

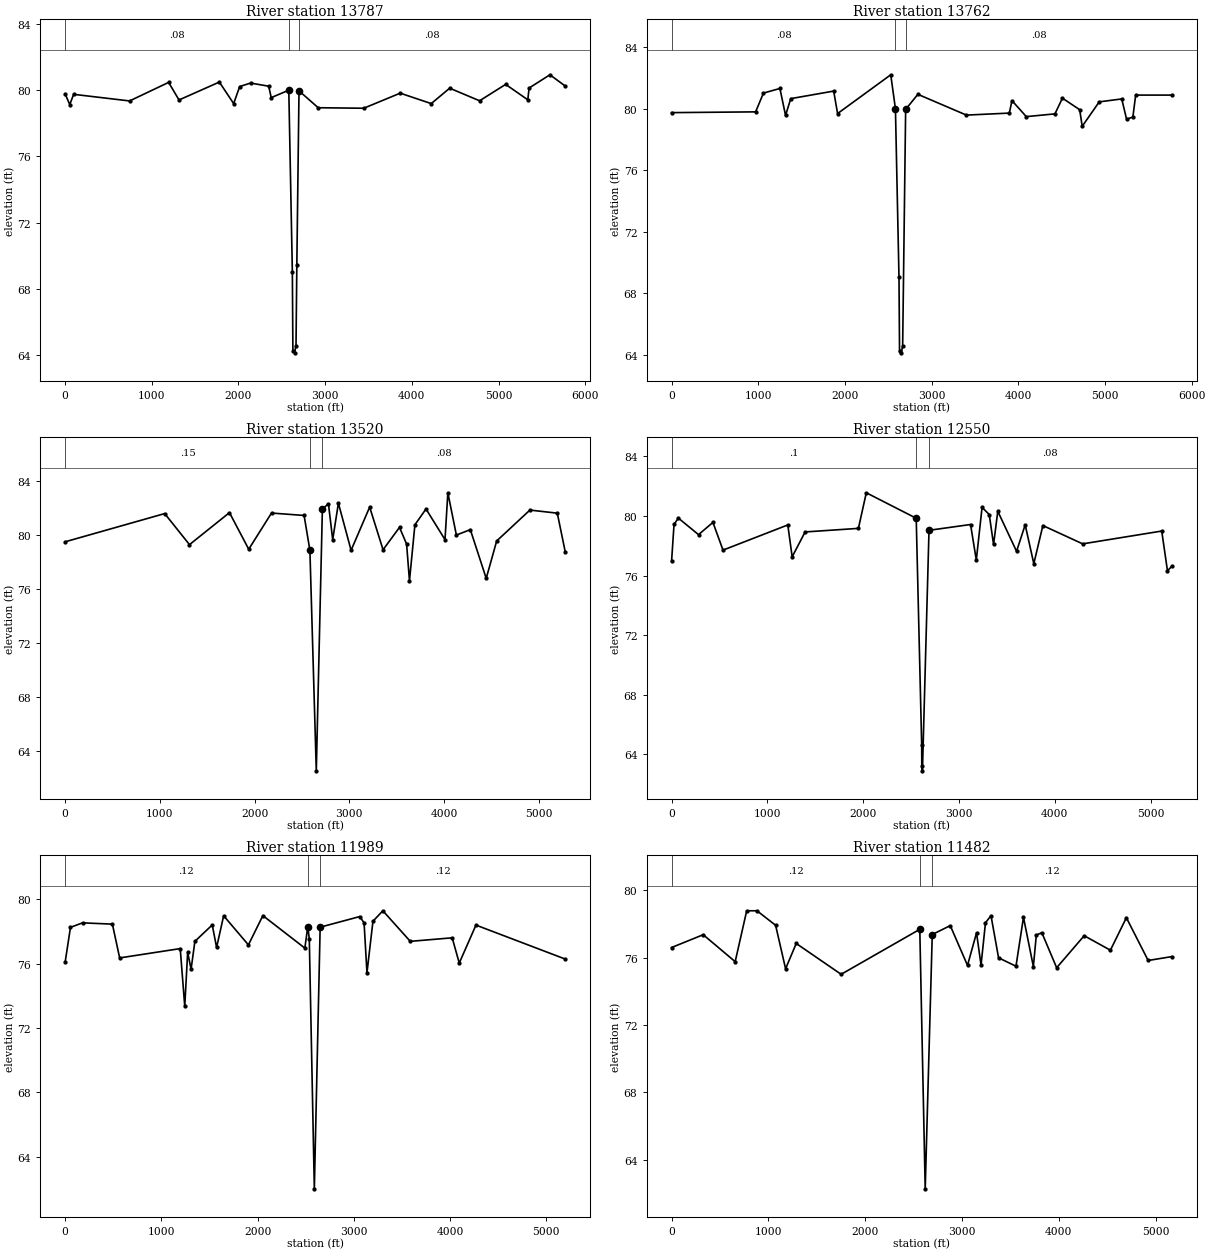
Type RM Length L Ch R = 1 ,13787   ,25.44,25.49,25.53
BEGIN DESCRIPTION:
13787.72
END DESCRIPTION:
XS GIS Cut Line= 6
     3046345.326    13818991.012     3046424.392    13816449.708
     3046426.296     13816263.18      3046425.73     13816238.73
      3046425.73     13816161.88     3046572.072    13813226.189
#Sta/Elev= 30
       0   79.78   53.54   79.13   98.56   79.75  743.87   79.35 1194.09   80.47
 1314.15   79.41 1779.37   80.49 1944.45   79.19 2014.03   80.22 2139.55   80.43
 2348.78   80.24 2377.89   79.55 2580.59      80 2621.57   69.05    2628   64.23
 2646.93   64.14 2663.86   64.57 2673.24   69.43 2698.44   79.96 2919.87   78.94
 3445.52   78.91 3866.04   79.82 4223.88   79.19 4436.75   80.12 4781.79   79.36
 5082.21   80.35 5337.87   79.42 5352.89   80.13 5593.18   80.93 5769.71   80.25
#Mann= 3 , 0 , 0
       0     .08       0 2580.59    .015       0 2698.44     .08       0
#XS Ineff= 2 , 0
       0    2552            2726       0
Permanent Ineff=
       T       T
Bank Sta=2580.59,2698.44
XS Rating Curve= 0
Exp/Cntr=.5,.3

Type RM Length L Ch R = 1 ,13762   ,240.69,242.39,245.29
BEGIN DESCRIPTION:
13762.23
END DESCRIPTION:
XS GIS Cut Line= 6
     3046366.588    13818991.657     3046449.889    13816448.878
     3046451.793    13816262.349     3046451.228      13816237.9
     3046451.228     13816161.05     3046608.963    13813227.545
#Sta/Elev= 30
       0   79.75  969.68    79.8 1059.73   81.02 1249.82   81.32 1314.86   79.57
 1374.89   80.66 1870.16   81.15 1915.18   79.69 2528.63   82.21 2582.59      80
 2623.57   69.05    2630   64.23 2648.93   64.14 2665.86   64.57 2700.44   79.96
 2841.32   80.94 3401.36   79.59  3896.2   79.72 3927.12   80.53 4092.35   79.49
 4422.83   79.67 4509.17   80.69 4708.24   79.94 4737.26   78.86 4933.57   80.45
 5193.42   80.64 5249.02   79.33 5321.72   79.46 5354.17   80.89 5769.73   80.89
#Mann= 3 , 0 , 0
       0     .08       0 2582.59     .04       0 2700.44     .08       0
#XS Ineff= 2 , 0
       0    2549            2733       0
Permanent Ineff=
       T       T
Bank Sta=2582.59,2700.44
XS Rating Curve= 0
Exp/Cntr=.3,.1

Type RM Length L Ch R = 1 ,13520   ,969.27,969.91,970.96
BEGIN DESCRIPTION:
13519.84
END DESCRIPTION:
XS GIS Cut Line= 4
     3046516.226    13818996.194     3046690.672     13816460.48
     3046694.629    13816286.423     3046761.208    13813723.824
#Sta/Elev= 30
       0   79.49 1051.17   81.58 1312.95   79.28 1734.98   81.65 1938.27   78.94
 2178.83   81.62 2522.77   81.44 2584.05   78.86 2651.52   62.53 2715.81   81.92
 2779.75    82.3 2824.77   79.65 2884.79   82.35 3018.84   78.86  3214.9   82.06
 3356.18    78.9    3530   80.56 3604.81   79.32 3635.04    76.6 3692.56   80.75
 3809.56   81.92 4010.16   79.65 4040.17   83.12  4130.2   79.99 4277.56   80.39
 4445.31   76.78 4555.44   79.55 4906.44   81.84 5195.56   81.61 5279.26   78.75
#Mann= 3 , 0 , 0
       0     .15       0 2584.05     .04       0 2715.81     .08       0
#XS Ineff= 2 , 0
       0    2541            2841       0
Permanent Ineff=
       T       T
Bank Sta=2584.05,2715.81
XS Rating Curve= 0
Exp/Cntr=.3,.1

Type RM Length L Ch R = 1 ,12550   ,557.53,560.85,562.98
BEGIN DESCRIPTION:
12549.93
END DESCRIPTION:
XS GIS Cut Line= 5
     3047504.102    13818978.122     3047634.914    13817087.366
     3047660.134    13816450.209     3047663.894    13816296.134
      3047714.91    13813763.504
#Sta/Elev= 30
       0   76.96   25.68   79.44   70.79   79.86  281.29   78.75  431.65   79.57
   536.9   77.71 1213.18    79.4 1258.62   77.26 1393.95   78.93 1950.18   79.17
 2032.41   81.56 2553.53   79.85 2610.63   64.61 2611.78   63.21 2618.57   62.89
 2687.05   79.04 3120.77   79.43 3180.79   77.04  3240.8   80.58 3315.81    80.1
 3360.82   78.09 3404.98   80.32 3600.87   77.63 3690.89   79.41 3780.91    76.8
  3875.6   79.36 4291.01   78.13 5116.18   78.99 5176.19   76.32  5220.2   76.62
#Mann= 3 , 0 , 0
       0      .1       0 2553.53     .04       0 2687.05     .08       0
#XS Ineff= 2 , 0
       0    2519            2753       0
Permanent Ineff=
       T       T
Bank Sta=2553.53,2687.05
XS Rating Curve= 0
Exp/Cntr=.3,.1

Type RM Length L Ch R = 1 ,11989   ,493.6,507.21,485.78
BEGIN DESCRIPTION:
11989.08
END DESCRIPTION:
XS GIS Cut Line= 5
     3048050.448    13818978.122     3048204.134    13816656.326
     3048219.658    13816462.285     3048225.057    13816318.393
     3048320.736     13813788.71
#Sta/Elev= 30
       0   76.08   55.74   78.26  181.11   78.54   491.3   78.46  566.86   76.36
 1196.27   76.94 1243.34   73.35  1273.4   76.71 1309.07   75.66 1348.57   77.39
 1528.96   78.41 1574.06   77.01 1647.46   78.98 1904.78   77.17 2055.11   78.99
 2491.23   76.97 2521.54   78.29 2537.44   77.56 2589.83   62.01 2650.32   78.27
 3061.71   78.93 3106.74   78.54 3136.76   75.44 3199.08   78.64 3301.88   79.29
 3587.08   77.39 4022.39   77.61 4095.83   76.04  4269.4    78.4 5197.02   76.29
#Mann= 3 , 0 , 0
       0     .12       0 2521.54     .04       0 2650.32     .12       0
#XS Ineff= 2 , 0
       0    2486            2670       0
Permanent Ineff=
       T       T
Bank Sta=2521.54,2650.32
XS Rating Curve= 0
Exp/Cntr=.3,.1

Type RM Length L Ch R = 1 ,11482   ,209.28,192.17,212.46
BEGIN DESCRIPTION:
11481.87
END DESCRIPTION:
XS GIS Cut Line= 6
     3048527.538     13819008.89     3048632.096    13816762.257
      3048727.44    13816479.591     3048731.276    13816333.892
     3048593.089    13815825.749        3048649.     13813879.46
#Sta/Elev= 30
       0    76.6  326.74   77.36   657.1   75.76  776.11   78.78  882.34   78.78
 1074.68   77.92 1177.87   75.34 1287.78   76.84 1751.81   75.01 2564.37   77.68
 2620.35   62.28 2693.13   77.37    2879    77.9 3057.28   75.54 3150.55   77.47
 3197.18   75.56 3242.98   78.07 3300.11   78.49 3378.04   75.99 3558.11   75.49
 3635.61   78.39 3737.72   75.47  3768.2   77.34 3825.25   77.48 3978.29    75.4
 4262.86    77.3 4533.52   76.44 4698.58   78.37 4923.68   75.83 5166.82   76.06
#Mann= 3 , 0 , 0
       0     .12       0 2564.37     .04       0 2693.13     .12       0
#XS Ineff= 2 , 0
       0    2489            2700       0
Permanent Ineff=
       T       T
Bank Sta=2564.37,2693.13
XS Rating Curve= 0
Exp/Cntr=.3,.1