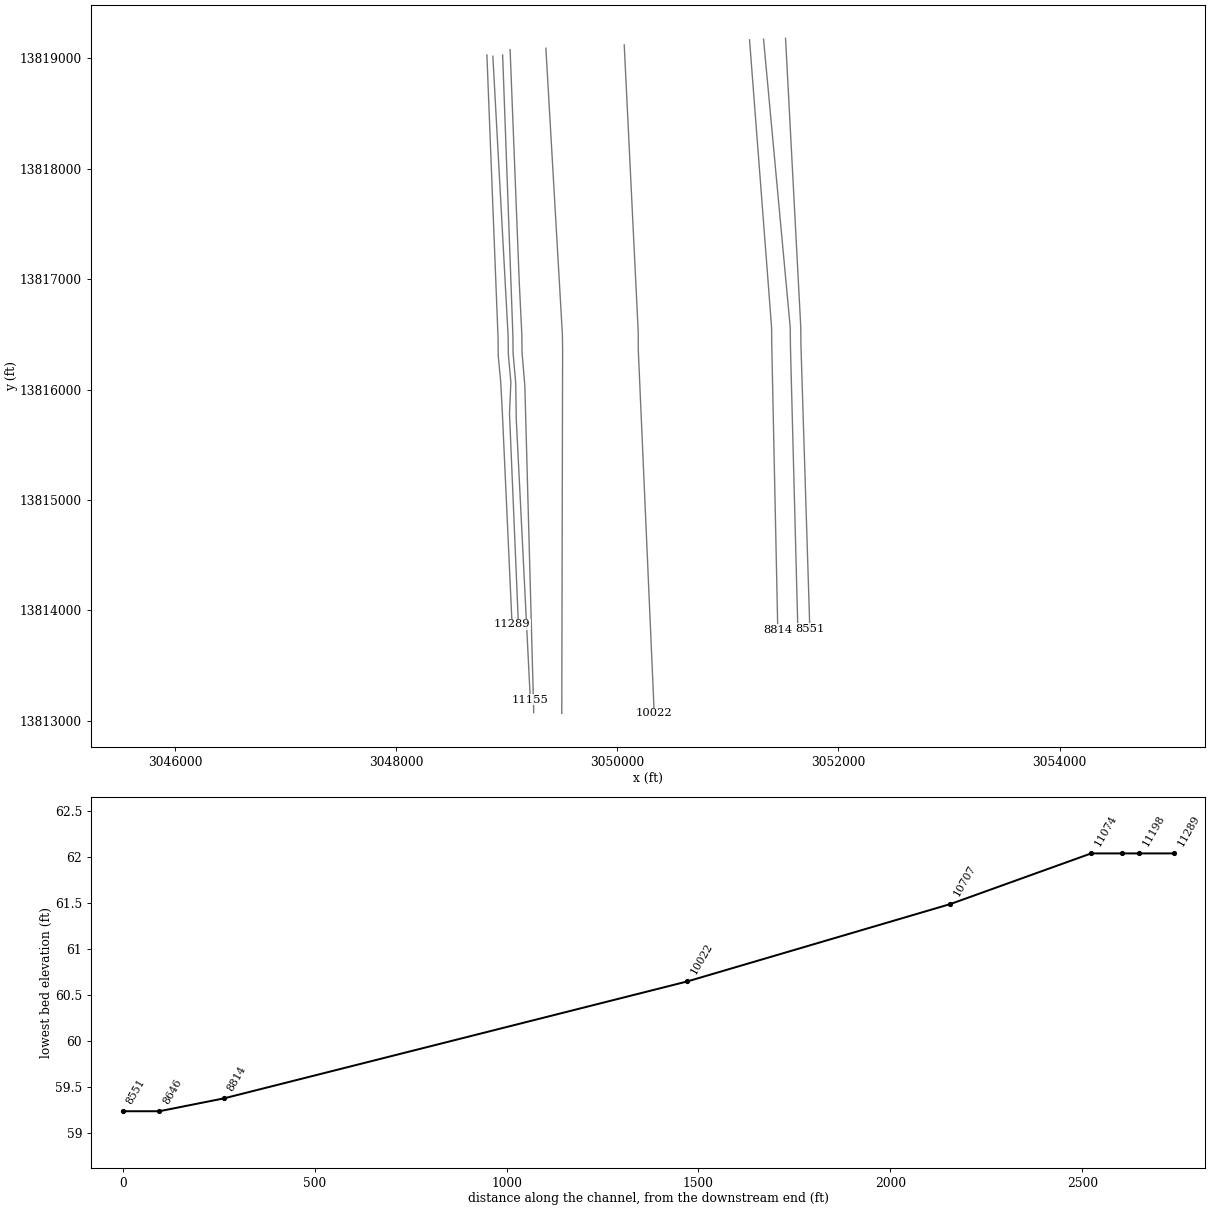
HEC-RAS study D122-00-00.prj: D122-00-00

--- D122-00-00.g04 (geometry) --- (continued)

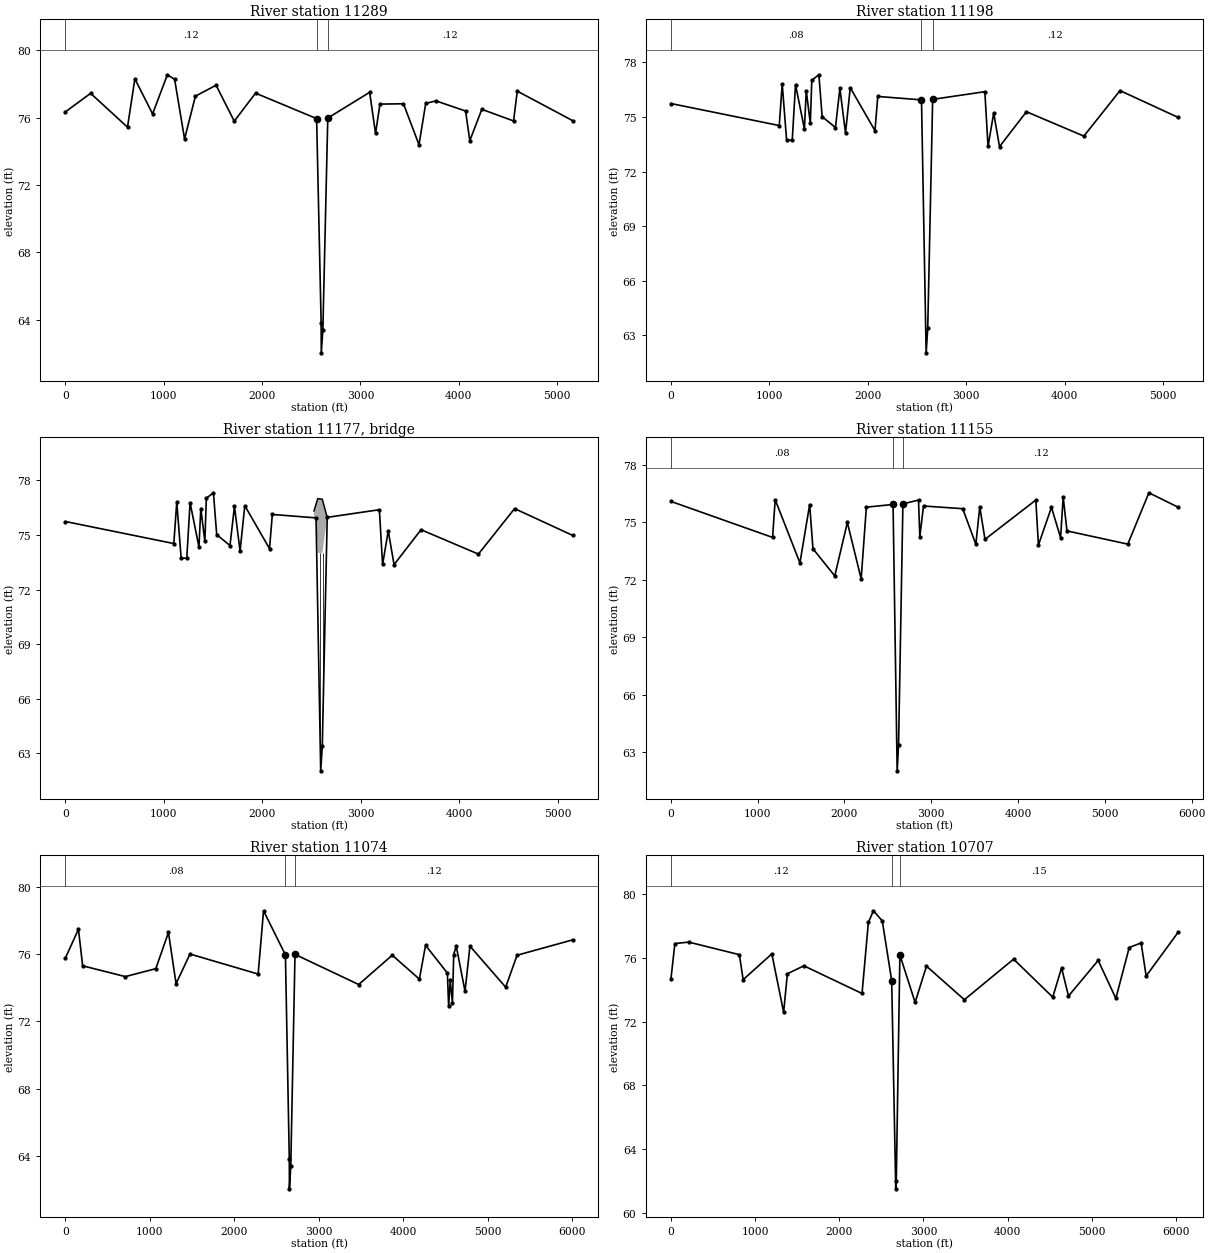
Type RM Length L Ch R = 1 ,11289   ,90.71,91.21,92.37
BEGIN DESCRIPTION:
11289.70
END DESCRIPTION:
XS GIS Cut Line= 6
     3048819.949     13819028.12     3048920.904     13816465.14
     3048922.756    13816304.105     3048944.123    13816077.928
     3048958.728    13815812.853     3049047.417    13813875.439
#Sta/Elev= 30
       0   76.34  255.82   77.44  631.11   75.43  705.93    78.3  886.31   76.22
 1036.42   78.54 1110.33   78.27 1211.43   74.73 1321.64   77.27 1531.81   77.92
 1716.92   75.79 1933.57   77.45 2554.69   75.94 2600.61   63.82  2601.9   62.04
 2618.03   63.38 2668.16   75.97 3093.84    77.5 3153.93   75.06    3199    76.8
    3438   76.82 3595.94   74.39 3664.49   76.84 3768.24   76.99 4069.77   76.39
 4112.85   74.63 4235.09   76.49 4557.96    75.8 4595.47   77.57 5158.12   75.82
#Mann= 3 , 0 , 0
       0     .12       0 2554.69     .04       0 2668.16     .12       0
#XS Ineff= 2 , 0
       0    2483            2692       0
Permanent Ineff=
       T       T
Bank Sta=2554.69,2668.16
XS Rating Curve= 0
Exp/Cntr=.5,.3

Type RM Length L Ch R = 1 ,11198   ,44.41,43.1,43.55
BEGIN DESCRIPTION:
11198.49
END DESCRIPTION:
XS GIS Cut Line= 6
     3048873.814    13819016.582     3049011.904    13816483.872
     3049013.756    13816322.837     3049036.775    13816064.695
     3049024.332    13815783.047     3049105.129    13813871.593
#Sta/Elev= 30
       0   75.74 1100.71   74.53 1130.76   76.81 1175.51   73.72  1232.5   73.73
 1265.96   76.78 1356.09   74.34 1374.95   76.45 1416.18   74.65  1431.2   77.02
 1503.16   77.32 1536.36   75.02 1671.56   74.42 1716.63   76.57 1773.83   74.12
 1821.78   76.61 2072.99   74.25 2101.48   76.13 2545.69   75.94  2592.9   62.04
 2609.03   63.38 2659.16   75.97  3189.1   76.39 3221.55   73.38 3279.19   75.22
  3338.2   73.37 3611.89   75.29 4195.01   73.95 4562.59   76.45 5151.77   74.98
#Mann= 3 , 0 , 0
       0     .08       0 2545.69    .015       0 2659.16     .12       0
#XS Ineff= 2 , 0
       0    2453            2683       0
Permanent Ineff=
       T       T
Bank Sta=2545.69,2659.16
XS Rating Curve= 0
Exp/Cntr=.5,.3

Type RM Length L Ch R = 3 ,11177   ,,,
BEGIN DESCRIPTION:
Cook Road Bridge
END DESCRIPTION:
Bridge Culvert--1,0,-1,-1, 0
Deck Dist Width WeirC Skew NumUp NumDn MinLoCord MaxHiCord MaxSubmerge Is_Ogee
5,25,2.6,0, 4, 4, , , .95, 0, 0,0,,
 2524.56 2563.15 2608.65 2659.16
   76.32      77   76.97   75.97
   74.04   74.02   73.99   74.04
 2538.56 2576.16 2621.66 2673.16
   76.35      77   76.97   75.97
   74.04   74.02   73.99   74.04
Pier Skew, UpSta & Num, DnSta & Num=  ,2586.48, 2 ,2599.49, 2 , 0 , 0 , 0 ,,
     1.2     1.2
     -.4   74.02
     1.2     1.2
     -.4   74.02
Pier Skew, UpSta & Num, DnSta & Num=  ,2616.82, 2 ,2629.83, 2 , 0 , 0 , 0 ,,
     1.2     1.2
       0   74.42
     1.2     1.2
       0   74.42
BR Coef=-1 , 1 , 1 ,1.25, 0 ,,,.8,-1,2,0,
WSPro=,,,, 1 ,,,, 0 ,,,, 0 ,,,,-1 ,-1 ,-1 , 0 , 0 , 0 , 0 , 0
BC Design=,, 0 ,, 0 ,,,,,,

Type RM Length L Ch R = 1 ,11155   ,80.56,81.18,81.22
BEGIN DESCRIPTION:
11155.39
END DESCRIPTION:
XS GIS Cut Line= 6
     3048962.307     13819028.12      3049054.92     13816491.25
     3049056.772    13816330.215     3049080.426     13816059.78
     3049085.892    13815725.357     3049212.859    13813190.854
#Sta/Elev= 30
       0    76.1  1171.4   74.22 1201.42   76.19 1486.61   72.89 1598.56   75.93
 1636.71   73.63 1888.18   72.21    2033      75 2192.08   72.06 2252.12    75.8
 2559.69   75.94  2606.9   62.04 2623.03   63.38 2673.16   75.97  2852.9   76.17
 2867.96   74.26 2910.48   75.86 3362.24   75.72 3513.66   73.86 3558.72   75.82
 3618.79   74.12 4204.52   76.17 4234.56   73.82 4384.75   75.79 4489.88   74.21
 4519.92   76.33 4563.64   74.56 5264.45   73.87 5507.59   76.55 5843.22    75.8
#Mann= 3 , 0 , 0
       0     .08       0 2559.69    .015       0 2673.16     .12       0
#XS Ineff= 2 , 0
       0    2429            2694       0
Permanent Ineff=
       T       T
Bank Sta=2559.69,2673.16
XS Rating Curve= 0
Exp/Cntr=.5,.3

Type RM Length L Ch R = 1 ,11074   ,366.12,366.94,362.19
BEGIN DESCRIPTION:
11074.21
END DESCRIPTION:
XS GIS Cut Line= 6
     3049029.821    13819076.222     3049112.359    13816978.211
     3049136.052    13816495.337     3049137.904    13816334.302
      3049163.21    13816031.902      3049243.64    13813075.475
#Sta/Elev= 30
       0   75.76  153.84   77.46  203.56   75.29  709.08   74.65 1069.55   75.12
 1219.66   77.27 1309.73   74.23 1474.57   75.99 2281.78    74.8 2345.64   78.56
 2604.69   75.94 2650.61   63.82  2651.9   62.04 2668.03   63.38 2718.16   75.97
 3472.13   74.18 3869.85   75.92 4191.14    74.5 4264.16   76.51 4522.53   74.86
 4537.53   72.89 4556.24   74.43 4582.55    73.1 4597.56   75.96 4627.57   76.46
 4731.49   73.78  4789.9   76.46 5212.79   74.02 5347.84   75.92 6005.11   76.83
#Mann= 3 , 0 , 0
       0     .08       0 2604.69     .04       0 2718.16     .12       0
#XS Ineff= 2 , 0
       0    2431            2746       0
Permanent Ineff=
       T       T
Bank Sta=2604.69,2718.16
XS Rating Curve= 0
Exp/Cntr=.3,.1

Type RM Length L Ch R = 1 ,10707   ,686.92,685.25,687.62
BEGIN DESCRIPTION:
10707.27
END DESCRIPTION:
XS GIS Cut Line= 4
      3049353.43    13819089.519     3049502.922    13816495.961
     3049504.761      13816347.1     3049497.226    13813068.832
#Sta/Elev= 30
       0   74.67    47.1   76.91  212.37      77  813.37   76.21  858.13   74.64
 1199.08   76.26 1339.24   72.59 1383.76   75.01 1579.64   75.51 2270.78   73.77
 2345.91   78.24 2406.01   78.97 2511.18   78.34 2622.99   74.58 2671.12   61.49
 2677.58   62.01 2720.52   76.19 2901.34   73.21 3036.34   75.49 3486.34   73.38
 4071.34   75.93 4536.34   73.54 4641.34   75.38 4723.62   73.61 5076.34   75.85
 5286.34   73.46 5445.28   76.66 5586.34   76.95 5646.34   74.87 6025.01   77.61
#Mann= 3 , 0 , 0
       0     .12       0 2622.99     .04       0 2720.52     .15       0
#XS Ineff= 2 , 0
       0    2303          2728.5       0   75.25
Permanent Ineff=
       T       T
Bank Sta=2622.99,2720.52
XS Rating Curve= 0
Exp/Cntr=.3,.1

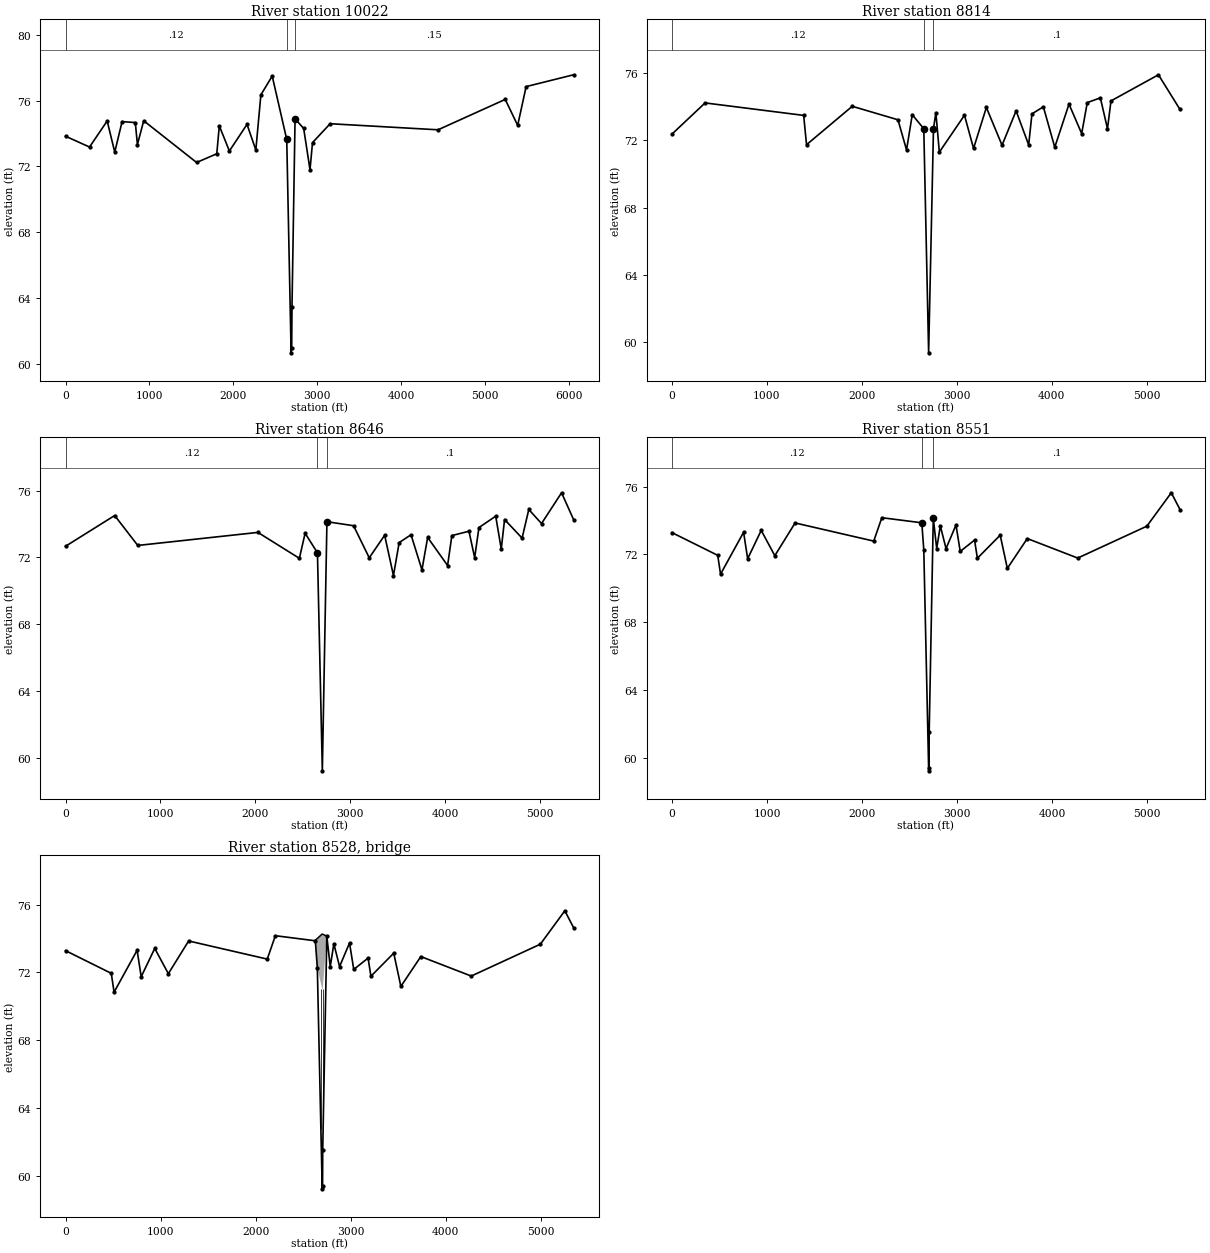
Type RM Length L Ch R = 1 ,10022   ,1206.71,1207.37,1206.4
BEGIN DESCRIPTION:
10022.02
END DESCRIPTION:
XS GIS Cut Line= 4
     3050062.079    13819118.636     3050189.037    13816511.311
     3050189.037    13816363.082     3050333.335    13813068.833
#Sta/Elev= 30
       0   73.84  286.47   73.18  496.72   74.77  586.83   72.87  674.55   74.73
  832.07   74.67  857.15   73.33  932.24   74.78 1562.42   72.24 1803.27   72.77
 1833.31   74.47 1953.45   72.94  2163.7   74.56 2268.82      73 2328.89   76.36
 2464.05    77.5 2637.22   73.64 2689.38   60.65 2696.18   60.92 2699.72   63.43
 2736.43    74.9  2839.3   74.31 2914.38    71.8  2944.4   73.45 3154.61    74.6
 4440.69   74.23  5241.6   76.08 5390.06    74.5 5490.75   76.86 6056.05   77.58
#Mann= 3 , 0 , 0
       0     .12       0 2637.22     .04       0 2736.43     .15       0
#XS Ineff= 2 , 0
       0    2533            2756       0
Permanent Ineff=
       T       T
Bank Sta=2637.22,2736.43
XS Rating Curve= 0
Exp/Cntr=.3,.1

Type RM Length L Ch R = 1 ,8814    ,167.83,168.66,168.95
BEGIN DESCRIPTION:
8814.656
END DESCRIPTION:
XS GIS Cut Line= 4
     3051195.484    13819165.205     3051394.773    13816563.675
     3051396.679     13816394.11     3051450.839    13813823.932
#Sta/Elev= 30
       0   72.36  348.72   74.21 1386.76   73.47 1416.84   71.73 1898.25   74.01
 2379.66   73.21 2469.92   71.42  2530.1   73.51 2651.47   72.68 2702.55   59.38
 2753.65   72.69 2778.73   73.63 2815.35   71.29 3079.88   73.48 3175.42   71.51
 3310.45   73.94 3475.49    71.7 3623.54   73.74 3755.79   71.72 3790.56   73.56
 3910.58   73.98 4030.61   71.58 4180.65   74.14 4314.15   72.39 4372.92   74.23
 4510.72   74.51 4585.74   72.68 4622.72   74.33 5122.31   75.88 5349.48   73.82
#Mann= 3 , 0 , 0
       0     .12       0 2651.47     .04       0 2753.65      .1       0
#XS Ineff= 2 , 0
       0    2610            2755       0
Permanent Ineff=
       T       T
Bank Sta=2651.47,2753.65
XS Rating Curve= 0
Exp/Cntr=.3,.1

Type RM Length L Ch R = 1 ,8646    ,96.76,95.13,95.65
BEGIN DESCRIPTION:
8645.991
END DESCRIPTION:
XS GIS Cut Line= 4
     3051322.133    13819170.409     3051563.426    13816561.897
     3051565.332    13816392.332     3051632.345    13813831.295
#Sta/Elev= 30
       0   72.67  517.78   74.51  761.14   72.72 2026.52    73.5 2463.38   71.95
 2523.64   73.45 2653.67   72.28  2705.2   59.24 2753.57   74.14 3034.14    73.9
  3199.2   71.98 3361.45   73.33 3454.28   70.92 3514.31   72.89 3639.28   73.36
 3754.39   71.26 3814.41    73.2 4024.48   71.52 4069.49   73.31 4249.56   73.57
 4309.58   71.99 4354.59   73.79 4531.25   74.47 4589.74   72.51 4624.69   74.27
 4809.08   73.16 4879.77   74.87  5013.8   74.03 5224.89   75.87 5351.14   74.27
#Mann= 3 , 0 , 0
       0     .12       0 2653.67     .04       0 2753.57      .1       0
#XS Ineff= 2 , 0
       0    2624            2768       0
Permanent Ineff=
       T       T
Bank Sta=2653.67,2753.57
XS Rating Curve= 0
Exp/Cntr=.5,.3

Type RM Length L Ch R = 1 ,8551    ,60.68,45.8,37.43
BEGIN DESCRIPTION:
8550.857
END DESCRIPTION:
XS GIS Cut Line= 4
     3051521.106    13819178.584     3051658.432    13816572.182
     3051660.338    13816402.617     3051740.629    13813835.688
#Sta/Elev= 30
       0   73.29  481.75   71.95  511.29   70.84  753.86   73.31  796.67   71.75
  939.36   73.42 1082.58   71.93 1296.08   73.86 2123.68   72.79 2209.15   74.17
  2629.7   73.87 2650.67   72.28  2702.2   59.24 2705.89   59.42 2707.56   61.55
 2750.57   74.14 2786.66   72.35 2824.73   73.69 2884.76   72.35 2989.81   73.74
 3034.04   72.18 3184.91   72.85 3214.93   71.78 3455.04   73.14 3530.08   71.18
 3740.18   72.94 4270.98   71.79 4998.59   73.67 5255.92   75.64 5347.78   74.65
#Mann= 3 , 0 , 0
       0     .12       0  2629.7    .015       0 2750.57      .1       0
#XS Ineff= 2 , 0
       0    2629            2781       0
Permanent Ineff=
       T       T
Bank Sta=2629.7,2750.57
XS Rating Curve= 0
Exp/Cntr=.5,.3

Type RM Length L Ch R = 3 ,8528    ,,,
BEGIN DESCRIPTION:
Kirkwood Bridge
END DESCRIPTION:
Bridge Culvert--1,0,-1,-1, 0
Deck Dist Width WeirC Skew NumUp NumDn MinLoCord MaxHiCord MaxSubmerge Is_Ogee
5,25,2.6,0, 3, 3, , , .95, 0, 0,0,,
  2629.7    2702 2750.57
    73.9   74.27   74.15
      71   71.02   70.97
 2624.55    2706 2754.58
   73.83   74.27   74.12
      71   71.02   70.97
Pier Skew, UpSta & Num, DnSta & Num=  ,2688.33, 2 ,2692.33, 2 , 0 , 0 , 0 ,,
     1.2     1.2
     -.3      71
     1.2     1.2
     -.3      71
Pier Skew, UpSta & Num, DnSta & Num=  ,2713.33, 2 ,2717.33, 2 , 0 , 0 , 0 ,,
     1.2     1.2
       0    71.3
     1.2     1.2
       0    71.3
BR Coef=-1 , 1 , 1 ,1.25, 0 ,,,.8,-1,2,0,
WSPro=,,,, 1 ,,,, 0 ,,,, 0 ,,,,-1 ,-1 ,-1 , 0 , 0 , 0 , 0 , 0
BC Design=,, 0 ,, 0 ,,,,,,