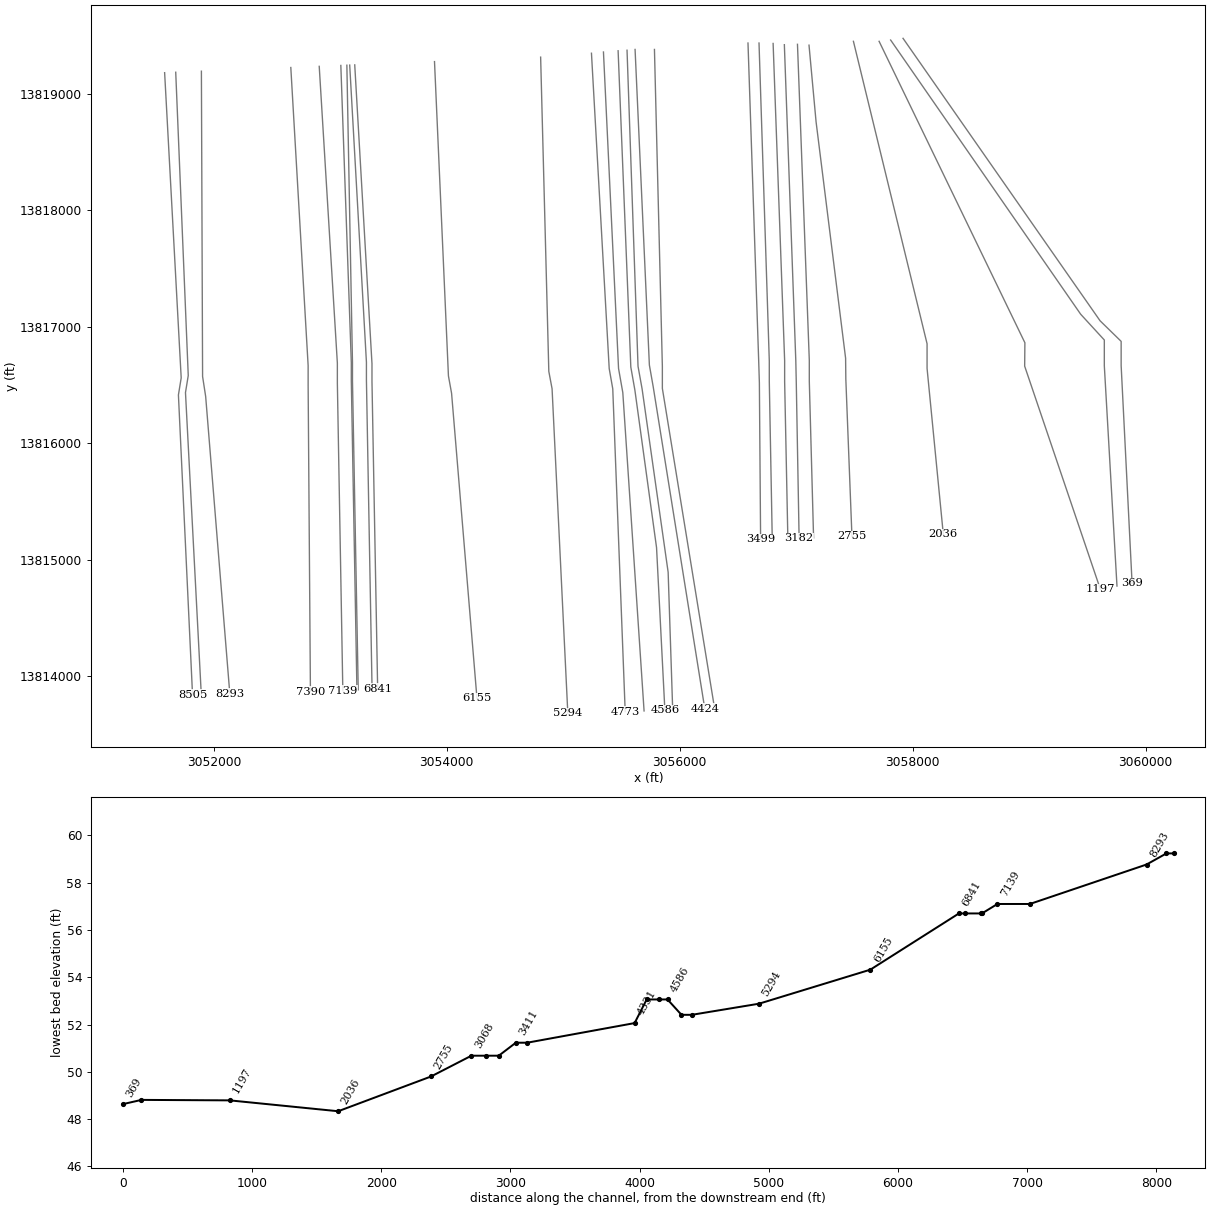
HEC-RAS study D122-00-00.prj: D122-00-00

--- D122-00-00.g04 (geometry) --- (continued)

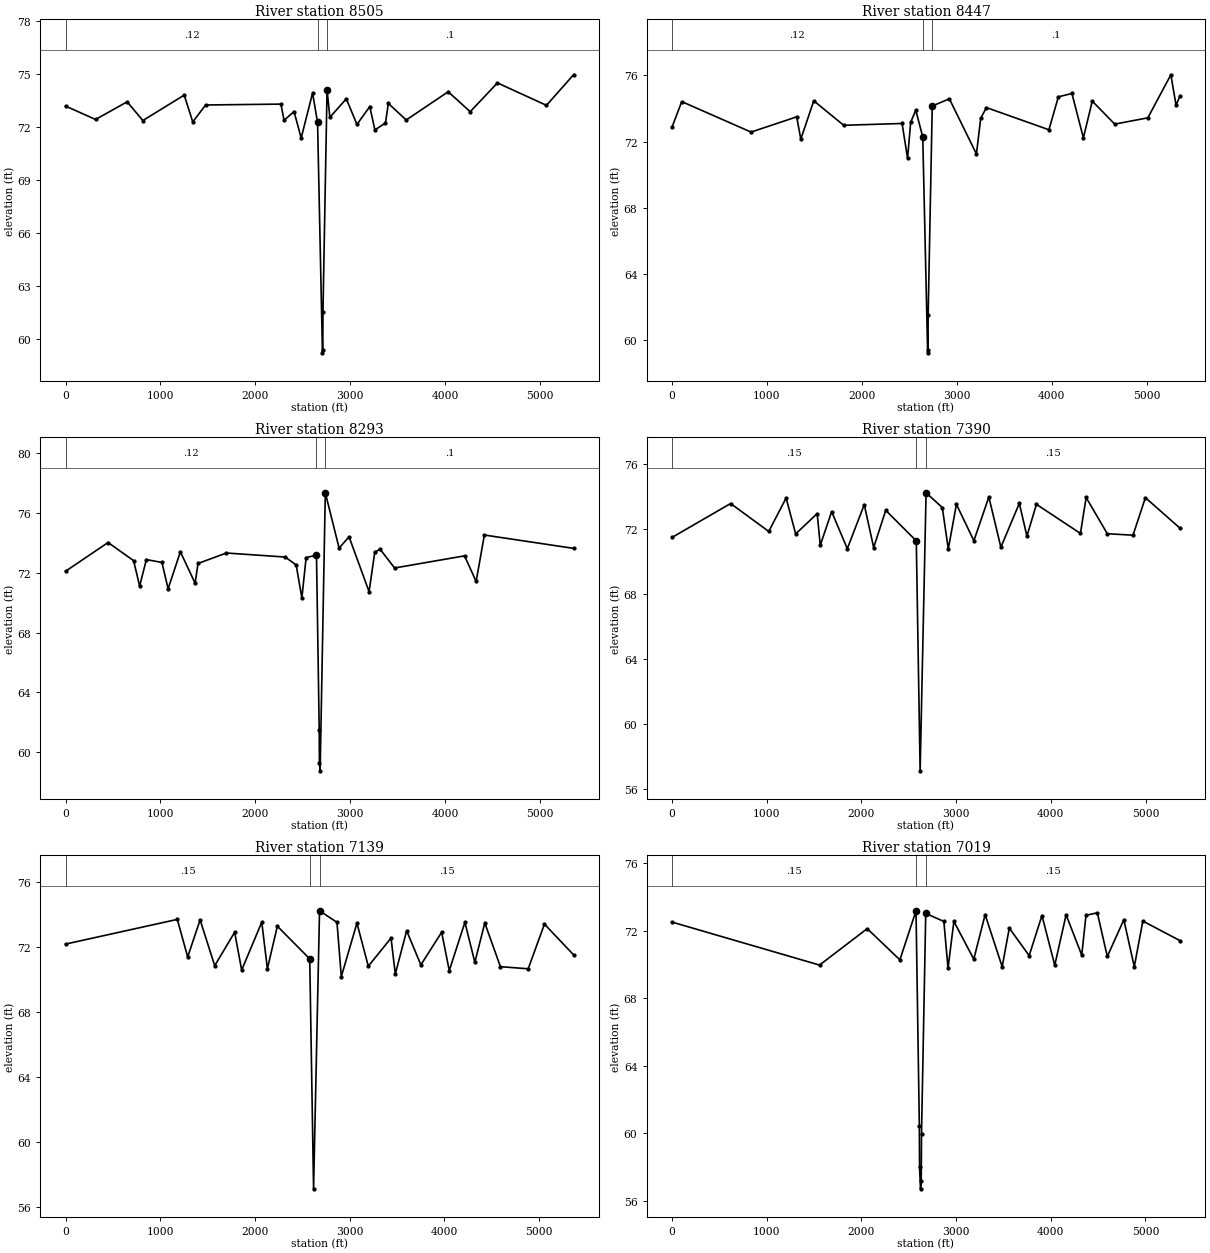
Type RM Length L Ch R = 1 ,8505    ,62.15,57.88,62.1
BEGIN DESCRIPTION:
8505.059
END DESCRIPTION:
XS GIS Cut Line= 4
     3051577.581    13819180.905       3051719.8    13816560.207
     3051696.003    13816413.826     3051817.225    13813838.795
#Sta/Elev= 30
       0   73.21  316.63   72.45  649.36   73.45   814.6   72.39 1250.24   73.83
 1340.37   72.31 1475.57   73.27 2268.72   73.32 2301.79    72.4 2406.94    72.9
 2482.05    71.4 2602.23   73.95 2654.67   72.28  2706.2   59.24 2709.89   59.42
 2711.56   61.55 2754.57   74.14  2784.2   72.57 2957.22   73.62 3069.51   72.17
 3204.66   73.18 3258.39   71.86 3369.84   72.25 3399.88   73.36 3588.24   72.42
 4030.57   74.02 4262.29   72.89 4549.12   74.52 5065.41   73.25 5350.74   74.98
#Mann= 3 , 0 , 0
       0     .12       0 2654.67    .015       0 2754.57      .1       0
#XS Ineff= 2 , 0
       0    2634            2790       0
Permanent Ineff=
       T       T
Bank Sta=2654.67,2754.57
XS Rating Curve= 0
Exp/Cntr=.5,.3

Type RM Length L Ch R = 1 ,8447    ,125,153.82,173.3
BEGIN DESCRIPTION:
8447.177
END DESCRIPTION:
XS GIS Cut Line= 4
     3051672.847    13819184.819     3051780.426    13816580.365
     3051756.629    13816433.984     3051892.357    13813840.986
#Sta/Elev= 30
       0   72.86  102.82   74.41  833.03   72.57 1313.87   73.49 1357.12   72.14
 1493.59   74.46 1808.86   72.98    2424   73.09 2481.67   70.98 2514.46   73.16
 2568.17   73.89 2641.67   72.28  2693.2   59.24 2696.89   59.42 2698.56   61.55
 2741.57   74.14 2921.69   74.58 3207.08   71.25 3252.14    73.4 3312.22   74.05
 3970.46   72.71 4070.37    74.7 4213.11    74.9 4333.62   72.22 4427.21   74.44
 4664.07   73.05 5012.42   73.43 5255.07   76.03 5309.96   74.19 5351.53   74.76
#Mann= 3 , 0 , 0
       0     .12       0 2641.67     .04       0 2741.57      .1       0
#XS Ineff= 2 , 0
       0    2639            2797       0
Permanent Ineff=
       T       T
Bank Sta=2641.67,2741.57
XS Rating Curve= 0
Exp/Cntr=.3,.1

Type RM Length L Ch R = 1 ,8293    ,910.02,902.92,884.77
BEGIN DESCRIPTION:
8293.352
END DESCRIPTION:
XS GIS Cut Line= 4
     3051893.329    13819193.878     3051903.539    13816572.498
     3051929.951    13816400.893     3052137.273     13813849.11
#Sta/Elev= 30
       0   72.09   448.8   74.01  717.76    72.8  781.38    71.1  852.24   72.87
  1016.6   72.68 1081.39   70.92 1210.84   73.39 1366.39   71.29 1396.39   72.61
 1696.39   73.31 2316.54   73.04  2431.4   72.51  2491.4   70.31  2536.4   73.01
 2645.58   73.16 2674.32   61.49 2676.39   59.28 2683.95   58.77 2738.64   77.33
 2883.71   73.64 2989.06   74.39 3199.75   70.73 3259.85   73.36 3315.53   73.57
 3468.63   72.31 4206.32   73.12 4328.45   71.41  4415.1   74.51 5355.22   73.62
#Mann= 3 , 0 , 0
       0     .12       0 2645.58     .04       0 2738.64      .1       0
#XS Ineff= 2 , 0
       0    2632            2785       0
Permanent Ineff=
       T       T
Bank Sta=2645.58,2738.64
XS Rating Curve= 0
Exp/Cntr=.3,.1

Type RM Length L Ch R = 1 ,7390    ,251.61,251.14,251.75
BEGIN DESCRIPTION:
7390.436
END DESCRIPTION:
XS GIS Cut Line= 4
     3052661.035    13819225.422     3052809.846    13816666.461
     3052809.846    13816495.103     3052829.436    13813866.321
#Sta/Elev= 30
       0   71.46  618.97   73.55 1021.79   71.83 1204.95   73.89 1305.78   71.68
 1532.98   72.93 1565.56   70.98 1685.77   73.05 1851.04   70.77 2029.96   73.48
 2129.36   70.84 2256.73   73.13 2579.26   71.25 2619.81    57.1 2682.74   74.21
 2854.01    73.3 2917.25   70.75 3002.91    73.5 3187.26   71.26 3345.36   73.95
 3472.27   70.86 3667.27   73.56 3747.38   71.54 3847.28    73.5 4312.29   71.71
 4372.29   73.92 4596.08   71.69  4867.3    71.6 4998.09   73.91 5363.49   72.03
#Mann= 3 , 0 , 0
       0     .15       0 2579.26     .04       0 2682.74     .15       0
#XS Ineff= 2 , 0
       0    2568            2725       0
Permanent Ineff=
       T       T
Bank Sta=2579.26,2682.74
XS Rating Curve= 0
Exp/Cntr=.3,.1

Type RM Length L Ch R = 1 ,7139    ,121.36,119.88,120.19
BEGIN DESCRIPTION:
7139.297
END DESCRIPTION:
XS GIS Cut Line= 4
     3052905.038    13819235.447      3053060.77    13816687.253
      3053060.77    13816515.895     3053107.715    13813875.288
#Sta/Elev= 30
       0   72.16 1180.59   73.68 1290.35   71.37 1421.35   73.65 1575.88   70.83
 1786.27   72.89 1860.39   70.56 2072.82   73.51 2131.92   70.64 2237.11   73.26
 2579.26   71.25 2619.81    57.1 2682.74   74.21 2866.92    73.5 2912.73   70.16
 3077.76   73.45 3197.78    70.8 3437.81   72.53 3482.82   70.32 3602.84   72.98
 3752.86   70.88 3972.44   72.89 4052.91   70.53 4217.94    73.5 4322.95   71.04
 4427.97   73.46    4593   70.77 4886.34   70.64 5058.07   73.39 5365.33    71.5
#Mann= 3 , 0 , 0
       0     .15       0 2579.26     .04       0 2682.74     .15       0
#XS Ineff= 2 , 0
       0    2567            2729       0
Permanent Ineff=
       T       T
Bank Sta=2579.26,2682.74
XS Rating Curve= 0
Exp/Cntr=.5,.3

Type RM Length L Ch R = 1 ,7019    ,10.91,10.01,10.04
BEGIN DESCRIPTION:
7019.419
END DESCRIPTION:
XS GIS Cut Line= 4
     3053090.623    13819243.073      3053180.57    13816690.814
      3053180.57    13816535.007     3053228.766    13813879.771
#Sta/Elev= 30
       0   72.52 1558.53   69.97 2061.85   72.13 2407.07   70.28 2577.34   73.19
 2612.44   60.44 2614.57   57.99 2624.94    56.7 2632.22   57.14 2635.37   59.96
 2679.96   73.03 2871.18   72.56 2915.39   69.78  2977.2   72.56 3187.24   70.32
 3307.25   72.96 3487.28   69.87  3562.3   72.16 3772.33   70.53 3907.35   72.91
 4042.38   69.96  4162.4   72.95 4327.42   70.56 4372.43   72.92 4492.03   73.07
 4597.47   70.48    4772   72.66 4882.52   69.87 4972.53   72.58 5365.32   71.42
#Mann= 3 , 0 , 0
       0     .15       0 2577.34     .04       0 2679.96     .15       0
#XS Ineff= 2 , 0
       0    2569            2732       0
Permanent Ineff=
       T       T
Bank Sta=2577.34,2679.96
XS Rating Curve= 0
Exp/Cntr=.5,.3

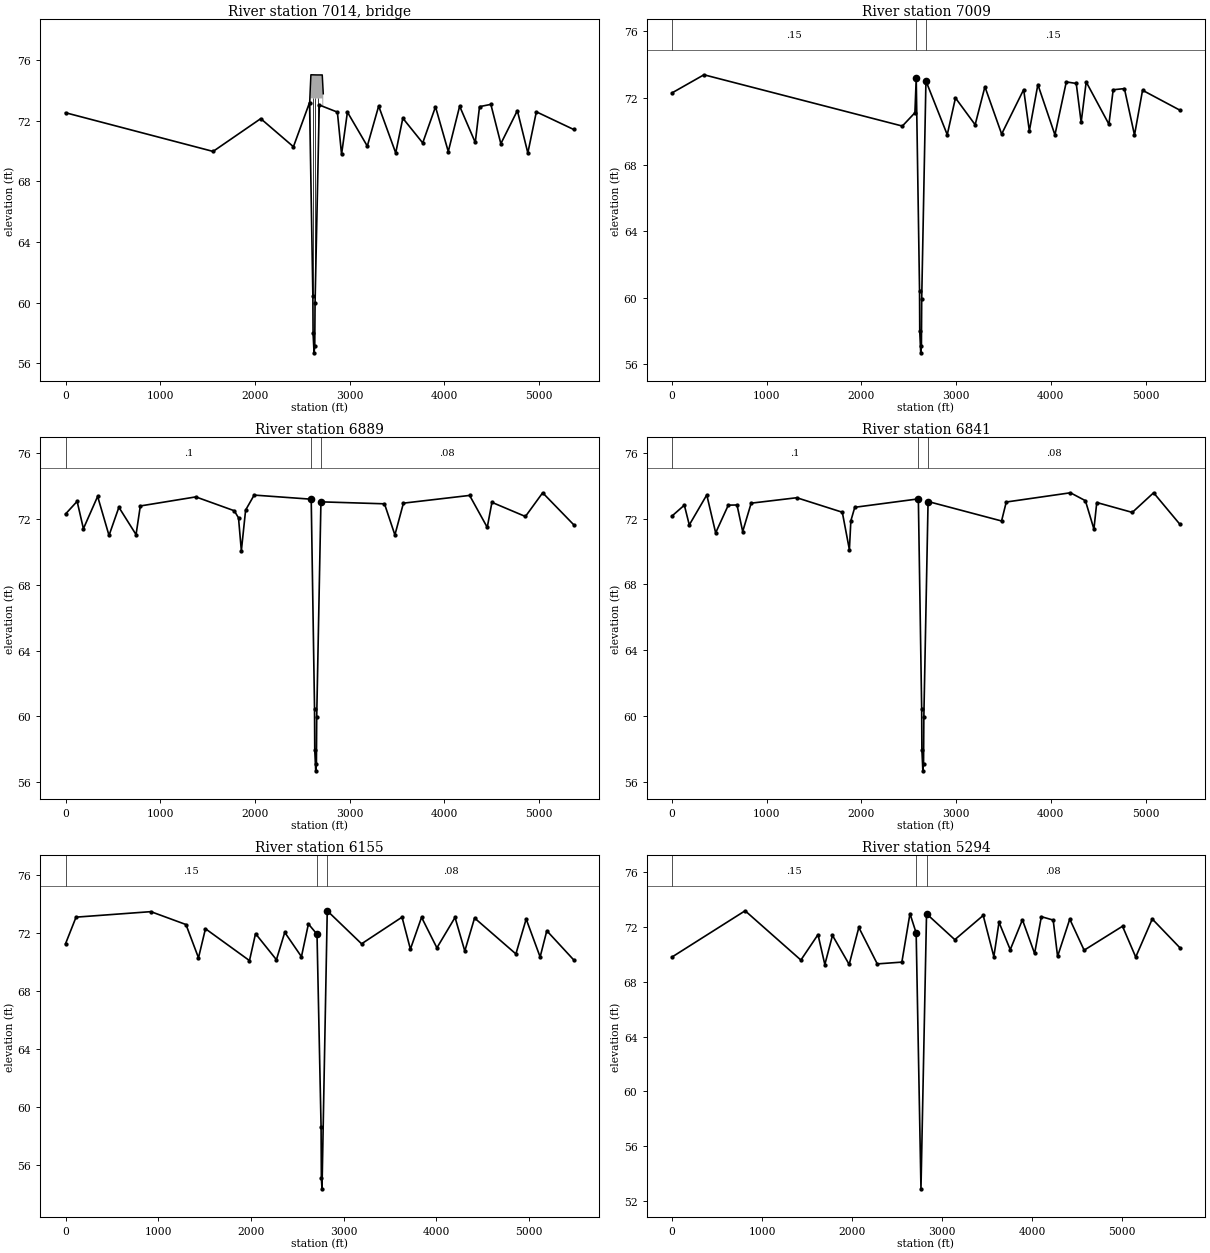
Type RM Length L Ch R = 3 ,7014    ,,,
BEGIN DESCRIPTION:
Crosswalk at Belle Park
END DESCRIPTION:
Bridge Culvert--1,0,-1,-1, 0
Deck Dist Width WeirC Skew NumUp NumDn MinLoCord MaxHiCord MaxSubmerge Is_Ogee
1,8,2.6,0, 5, 5, , , .95, 0, 0,0,,
 2577.35  2591.6  2651.5  2711.4 2722.16
   73.08   75.02   75.01   75.01   73.77
           73.47   73.46   73.46
 2578.35  2592.6  2652.5  2712.4 2723.16
   73.08   75.02   75.01   75.01   73.77
           73.47   73.46   73.46
Pier Skew, UpSta & Num, DnSta & Num=  ,2612.26, 2 ,2613.26, 2 , 0 , 0 , 0 ,,
     1.3     1.3
     -.3   73.47
     1.3     1.3
     -.3   73.47
Pier Skew, UpSta & Num, DnSta & Num=  ,2639.26, 2 ,2640.26, 2 , 0 , 0 , 0 ,,
     1.3     1.3
       0   73.77
     1.3     1.3
       0   73.77
Pier Skew, UpSta & Num, DnSta & Num=  ,2669.26, 2 ,2670.26, 2 , 0 , 0 , 0 ,,
     1.3     1.3
       0   73.77
     1.3     1.3
       0   73.77
BR Coef=-1 , 1 , 1 ,1.25, 0 ,,,.8,-1,2,0,
WSPro=,,,, 1 ,,,, 0 ,,,, 0 ,,,,-1 ,-1 ,-1 , 0 , 0 , 0 , 0 , 0
BC Design=,, 0 ,, 0 ,,,,,,

Type RM Length L Ch R = 1 ,7009    ,118.69,119.94,122.52
BEGIN DESCRIPTION:
7009.413
END DESCRIPTION:
XS GIS Cut Line= 4
      3053142.38    13819245.199      3053190.57    13816691.111
      3053190.57    13816535.304     3053239.974    13813882.013
#Sta/Elev= 30
       0   72.31  337.76    73.4 2432.37   70.32 2565.08   71.12 2578.84   73.19
 2613.94   60.44 2616.07   57.99 2626.44    56.7 2633.72   57.14 2636.87   59.96
 2681.46   73.03 2906.47    69.8  2993.2   72.01 3201.03    70.4 3304.13   72.68
 3480.87   69.84 3713.33   72.51 3773.34   70.03 3863.35   72.81 4043.38   69.79
 4163.41   72.97 4268.42   72.88 4320.39   70.54 4373.44   72.97 4613.48   70.43
 4658.49    72.5 4776.97   72.57 4883.53   69.78 4968.44   72.47  5364.1   71.27
#Mann= 3 , 0 , 0
       0     .15       0 2578.84     .04       0 2681.46     .15       0
#XS Ineff= 2 , 0
       0    2569            2733       0
Permanent Ineff=
       T       T
Bank Sta=2578.84,2681.46
XS Rating Curve= 0
Exp/Cntr=.5,.3

Type RM Length L Ch R = 1 ,6889    ,47.14,48.18,49.49
BEGIN DESCRIPTION:
6889.472
END DESCRIPTION:
XS GIS Cut Line= 4
     3053166.755    13819246.201      3053310.37    13816694.672
      3053310.37    13816538.865     3053358.783    13813886.496
#Sta/Elev= 30
       0   72.29  122.74   73.06     189    71.4  339.24   73.36  459.43   70.99
  563.66    72.7  744.88   71.04  789.95   72.78 1375.88   73.33 1781.52   72.49
 1826.59   72.06 1856.64   70.06 1901.71   72.53 1991.85   73.44 2594.34   73.19
 2629.44   60.44 2631.57   57.99 2641.94    56.7 2649.22   57.14 2652.37   59.96
 2696.96   73.03    3368   72.91 3477.87   71.02 3567.88   72.95 4266.74   73.42
 4453.03   71.48 4502.48      73 4856.08   72.14 5038.12   73.58 5364.18   71.65
#Mann= 3 , 0 , 0
       0      .1       0 2594.34     .04       0 2696.96     .08       0
#XS Ineff= 2 , 0
       0    2580            2744       0
Permanent Ineff=
       T       T
Bank Sta=2594.34,2696.96
XS Rating Curve= 0
Exp/Cntr=.3,.1

Type RM Length L Ch R = 1 ,6841    ,669.6,685.84,697.08
BEGIN DESCRIPTION:
6841.295
END DESCRIPTION:
XS GIS Cut Line= 4
     3053209.962    13819247.976     3053358.031    13816682.078
     3053358.031    13816526.271     3053406.763    13813888.738
#Sta/Elev= 30
       0   72.15  130.69   72.81  182.79   71.61  367.46   73.43  461.24   71.13
  594.74   72.81  686.62   72.82  746.72   71.21  836.23   72.93 1317.66   73.26
 1798.46   72.38 1873.21   70.11 1888.61   71.86 1930.03   72.68 2601.34   73.19
 2636.44   60.44 2638.57   57.99 2648.94    56.7 2656.22   57.14 2659.37   59.96
 2703.96   73.03 3479.87   71.85 3529.51      73 4207.11   73.56 4365.02   73.08
 4455.04   71.36 4485.04   72.97 4860.11   72.37 5085.15   73.56 5363.96   71.64
#Mann= 3 , 0 , 0
       0      .1       0 2601.34     .04       0 2703.96     .08       0
#XS Ineff= 2 , 0
       0    2577            2772       0
Permanent Ineff=
       T       T
Bank Sta=2601.34,2703.96
XS Rating Curve= 0
Exp/Cntr=.3,.1

Type RM Length L Ch R = 1 ,6155    ,863.99,861.59,860.97
BEGIN DESCRIPTION:
6155.450
END DESCRIPTION:
XS GIS Cut Line= 4
     3053894.902    13819276.119     3054014.539    13816577.262
     3054041.538    13816427.938     3054259.616    13813808.071
#Sta/Elev= 30
       0   71.24  113.73   73.08  921.32   73.46 1299.89   72.57 1435.03   70.27
  1510.1   72.28 1985.25   70.08 2050.63   71.94 2275.85   70.14 2365.94   72.03
 2545.97   70.35 2621.19   72.61 2713.97    71.9 2757.84   58.58 2760.94   55.06
 2767.91   54.32 2824.41   73.52 3194.87   71.24 3631.37   73.08 3721.68   70.87
  3842.1   73.07 4007.67   70.96 4203.34   73.06 4308.71   70.74 4414.07   73.02
  4860.1   70.54 4970.99   72.95 5121.51   70.33 5193.58   72.14 5482.18   70.14
#Mann= 3 , 0 , 0
       0     .15       0 2713.97     .04       0 2824.41     .08       0
#XS Ineff= 2 , 0
       0    2707            3218       0
Permanent Ineff=
       T       T
Bank Sta=2713.97,2824.41
XS Rating Curve= 0
Exp/Cntr=.3,.1

Type RM Length L Ch R = 1 ,5294    ,517.38,520.15,519.99
BEGIN DESCRIPTION:
5293.864
END DESCRIPTION:
XS GIS Cut Line= 4
     3054806.208    13819314.485     3054876.436    13816616.242
     3054904.455    13816466.872     3055039.684    13813679.628
#Sta/Elev= 30
       0   69.81  812.26   73.19 1431.52   69.59 1621.63   71.45 1697.56   69.26
  1782.5   71.39 1967.65   69.27 2074.99   71.97 2279.73   69.31 2552.85   69.44
 2642.88   72.98 2711.62   71.57 2765.05   52.88 2826.84   72.97 3140.84   71.08
 3456.21   72.85 3574.35   69.84 3631.64   72.35 3756.57   70.35 3891.73   72.53
 4026.89   70.07 4101.97   72.76  4233.2   72.51 4282.18   69.86 4417.34   72.58
 4576.94   70.31 5003.03   72.06 5149.85   69.81 5333.42   72.59 5641.66   70.48
#Mann= 3 , 0 , 0
       0     .15       0 2711.62     .04       0 2826.84     .08       0
#XS Ineff= 2 , 0
       0    2702            3251       0
Permanent Ineff=
       T       T
Bank Sta=2711.62,2826.84
XS Rating Curve= 0
Exp/Cntr=.3,.1

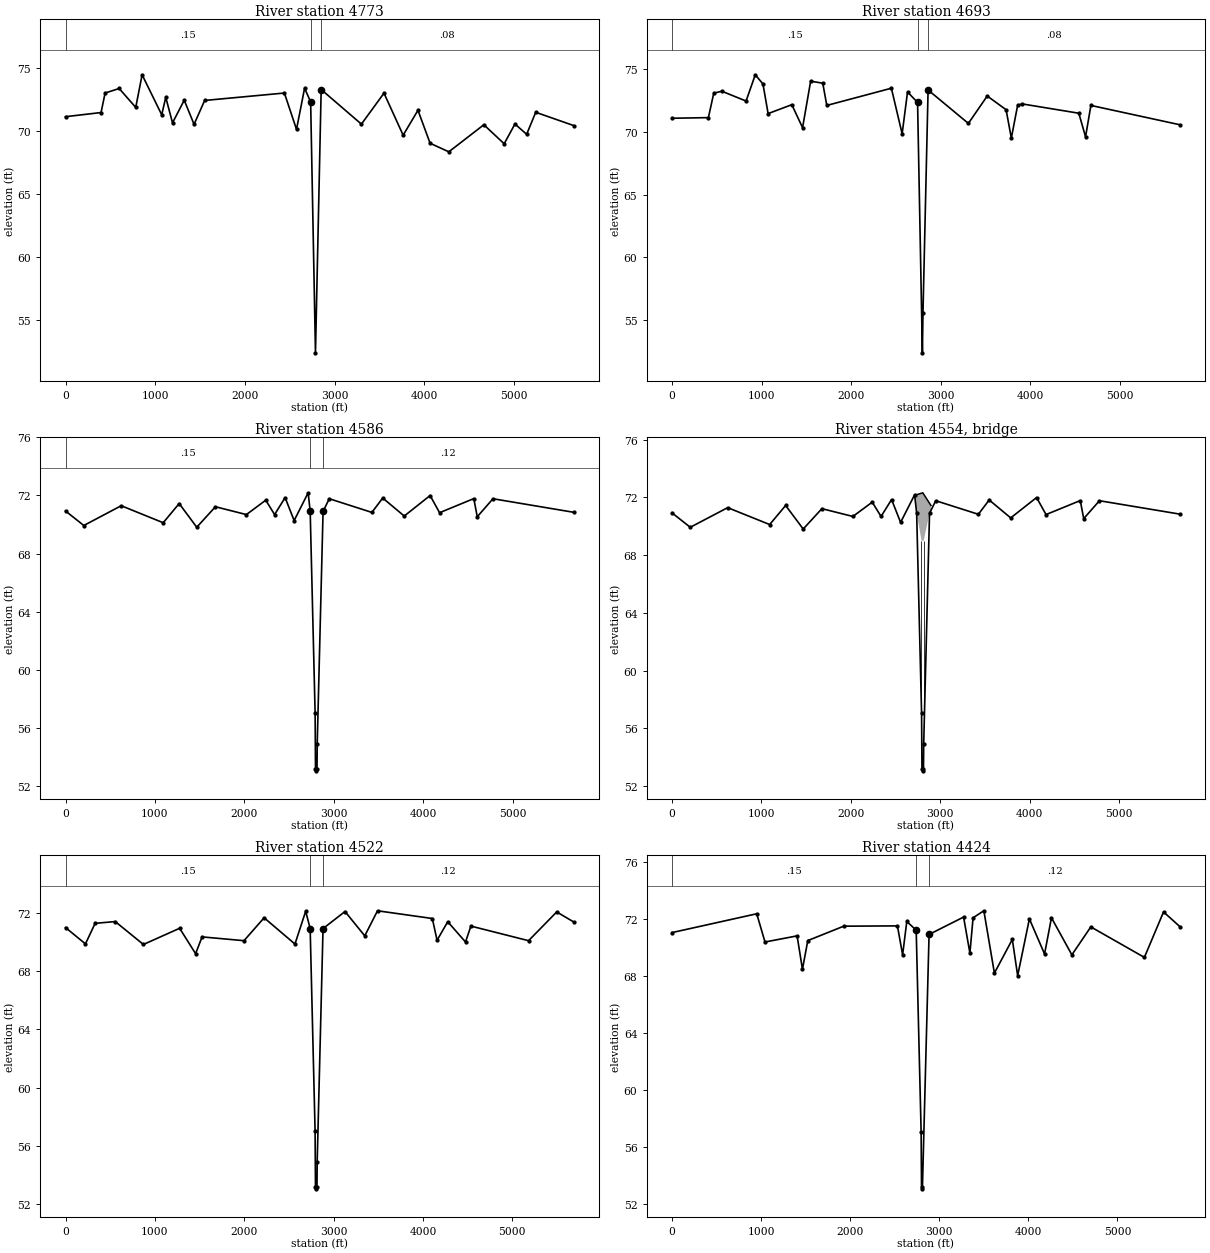
Type RM Length L Ch R = 1 ,4773    ,80.69,80.05,85.3
BEGIN DESCRIPTION:
4773.713
END DESCRIPTION:
XS GIS Cut Line= 4
     3055242.647    13819348.115     3055394.992     13816640.26
     3055425.494    13816466.855     3055532.293     13813694.85
#Sta/Elev= 30
       0   71.17  396.24    71.5  441.31   73.05  597.83   73.41  782.74   71.91
  853.85    74.5 1072.31   71.32 1117.38   72.71  1192.5   70.68 1323.23   72.48
 1432.88   70.56 1550.81   72.46 2439.47   73.05 2574.68   70.16 2664.82   73.44
 2732.13   72.34 2785.93   52.41 2849.46   73.33 3297.86   70.58 3549.59   73.04
 3763.21    69.7 3928.33   71.68 4063.43   69.06 4272.31   68.38 4662.57   70.53
 4889.04   69.02 5009.13   70.59 5139.56   69.77 5240.74   71.52 5662.27   70.47
#Mann= 3 , 0 , 0
       0     .15       0 2732.13     .04       0 2849.46     .08       0
#XS Ineff= 2 , 0
       0    2730            3087       0
Permanent Ineff=
       T       T
Bank Sta=2732.13,2849.46
XS Rating Curve= 0
Exp/Cntr=.3,.1

Type RM Length L Ch R = 1 ,4693    ,106.21,107.87,107.03
BEGIN DESCRIPTION:
4693.662
END DESCRIPTION:
XS GIS Cut Line= 6
     3055345.632     13819358.52     3055475.208     13816641.45
     3055480.872    13816609.121     3055490.391    13816555.299
     3055511.791    13816433.847     3055694.435    13813700.584
#Sta/Elev= 30
       0   71.08  406.48   71.13  466.55   73.08  556.99   73.23  826.96   72.45
  929.66   74.54 1015.66   73.81 1072.99   71.45 1337.54   72.16 1457.67   70.33
 1547.78   74.03 1682.93   73.87 1727.98    72.1  2448.8   73.47 2568.94   69.84
    2629   73.17 2741.13   72.34 2794.93   52.41 2801.53   55.62 2858.46   73.33
 3308.14   70.67 3518.61   72.85 3729.08   71.76 3787.79    69.5 3858.25   72.12
 3909.48   72.22 4540.89   71.48 4616.05    69.6 4675.57    72.1 5670.32   70.56
#Mann= 3 , 0 , 0
       0     .15       0 2741.13     .04       0 2858.46     .08       0
#XS Ineff= 2 , 0
       0    2739            3024       0
Permanent Ineff=
       T       T
Bank Sta=2741.13,2858.46
XS Rating Curve= 0
Exp/Cntr=.5,.3

Type RM Length L Ch R = 1 ,4586    ,62.35,63.75,63.28
BEGIN DESCRIPTION:
4586.788
END DESCRIPTION:
XS GIS Cut Line= 6
     3055471.473    13819369.182     3055580.566    13816653.394
     3055585.003    13816628.066     3055615.469    13816455.364
     3055801.508    13815103.136     3055872.972    13813706.897
#Sta/Elev= 30
       0   70.93  204.66   69.93   623.2   71.29 1092.56   70.12 1271.31   71.44
 1467.86   69.81 1676.76   71.22 2023.14   70.68 2239.62   71.67 2338.57   70.68
 2456.11   71.85 2557.13   70.27 2713.87   72.18 2736.66    70.9 2791.67   57.04
 2795.96    53.2 2805.82   53.06 2812.96   53.19 2815.32   54.93 2880.69    70.9
 2950.02   71.77 3426.66   70.83 3547.79   71.82 3788.56   70.58 4077.74   71.99
 4183.73   70.81 4566.58   71.78 4605.08   70.53  4780.9   71.77  5682.1   70.84
#Mann= 3 , 0 , 0
       0     .15       0 2736.66     .04       0 2880.69     .12       0
#XS Ineff= 2 , 0
       0    2730            2955       0
Permanent Ineff=
       T       T
Bank Sta=2736.66,2880.69
XS Rating Curve= 0
Exp/Cntr=.5,.3

Type RM Length L Ch R = 3 ,4554    ,,,
BEGIN DESCRIPTION:
Boone Road Bridge
END DESCRIPTION:
Bridge Culvert--1,0,-1,-1, 0
Deck Dist Width WeirC Skew NumUp NumDn MinLoCord MaxHiCord MaxSubmerge Is_Ogee
5,35,2.6,0, 3, 3, , , .95, 0, 0,0,,
 2713.87    2805 2896.58
   72.14   72.32   71.44
   68.96      69   68.99
 2714.98    2806 2916.19
      72   72.32   71.55
   68.96      69   68.99
Pier Skew, UpSta & Num, DnSta & Num=  ,2786.6, 2 ,2787.6, 2 , 0 , 0 , 0 ,,
    1.35    1.35
     -.4   71.99
    1.35    1.35
     -.4   71.99
Pier Skew, UpSta & Num, DnSta & Num=  ,2823.4, 2 ,2824.4, 2 , 0 , 0 , 0 ,,
    1.35    1.35
       0   72.39
    1.35    1.35
       0   72.39
BR Coef=-1 , 1 , 1 ,1.25, 0 ,,,.8,-1,2,0,
WSPro=,,,, 1 ,,,, 0 ,,,, 0 ,,,,-1 ,-1 ,-1 , 0 , 0 , 0 , 0 , 0
BC Design=,, 0 ,, 0 ,,,,,,

Type RM Length L Ch R = 1 ,4522    ,97.37,97.73,98.5
BEGIN DESCRIPTION:
4522.041
END DESCRIPTION:
XS GIS Cut Line= 5
     3055548.084    13819373.882      3055642.43    13816660.173
     3055677.365    13816466.175      3055901.09    13814891.608
     3055940.191    13813709.274
#Sta/Elev= 30
       0   70.97  223.18   69.85  331.58   71.26  556.72   71.38  871.91   69.81
 1277.15   70.92 1456.08   69.18 1528.61   70.33 1997.59   70.07 2222.72   71.64
 2567.93   69.84    2688   72.09 2738.16    70.9 2793.17   57.04 2797.46    53.2
 2807.32   53.06 2814.46   53.19 2816.82   54.93 2882.19    70.9 3128.29   72.07
 3349.18    70.4  3491.9   72.12 4105.33   71.59  4158.4    70.1 4277.79   71.37
 4476.69   69.98 4536.97   71.07 5182.33   70.07  5497.5   72.04 5685.83   71.36
#Mann= 3 , 0 , 0
       0     .15       0 2738.16     .04       0 2882.19     .12       0
#XS Ineff= 2 , 0
       0    2731            2927       0
Permanent Ineff=
       T       T
Bank Sta=2738.16,2882.19
XS Rating Curve= 0
Exp/Cntr=.5,.3

Type RM Length L Ch R = 1 ,4424    ,112.04,93.44,76.1
BEGIN DESCRIPTION:
4424.315
END DESCRIPTION:
XS GIS Cut Line= 6
     3055617.179    13819380.537     3055739.937    13816670.672
     3055752.271    13816600.788     3055754.644    13816587.153
     3055772.476    13816486.119     3056215.749    13813719.018
#Sta/Elev= 30
       0   71.03  951.28   72.35 1044.11   70.37 1404.48    70.8 1464.54   68.46
  1524.6   70.47 1928.08   71.48 2530.63    71.5 2588.85   69.47 2635.74   71.81
 2741.25    71.2 2796.67   57.04 2800.96    53.2 2810.82   53.06 2885.69    70.9
 3273.36   72.12 3344.05   69.59  3379.7   72.07 3500.79   72.56 3619.01   68.19
 3820.25   70.55 3880.11   68.01 4011.82   71.99 4182.04   69.53 4259.43   72.07
 4488.66   69.47 4701.34   71.43 5302.57   69.29  5517.6   72.48 5702.43   71.44
#Mann= 3 , 0 , 0
       0     .15       0 2741.25     .04       0 2885.69     .12       0
#XS Ineff= 2 , 0
       0    2723            2927       0
Permanent Ineff=
       T       T
Bank Sta=2741.25,2885.69
XS Rating Curve= 0
Exp/Cntr=.3,.1

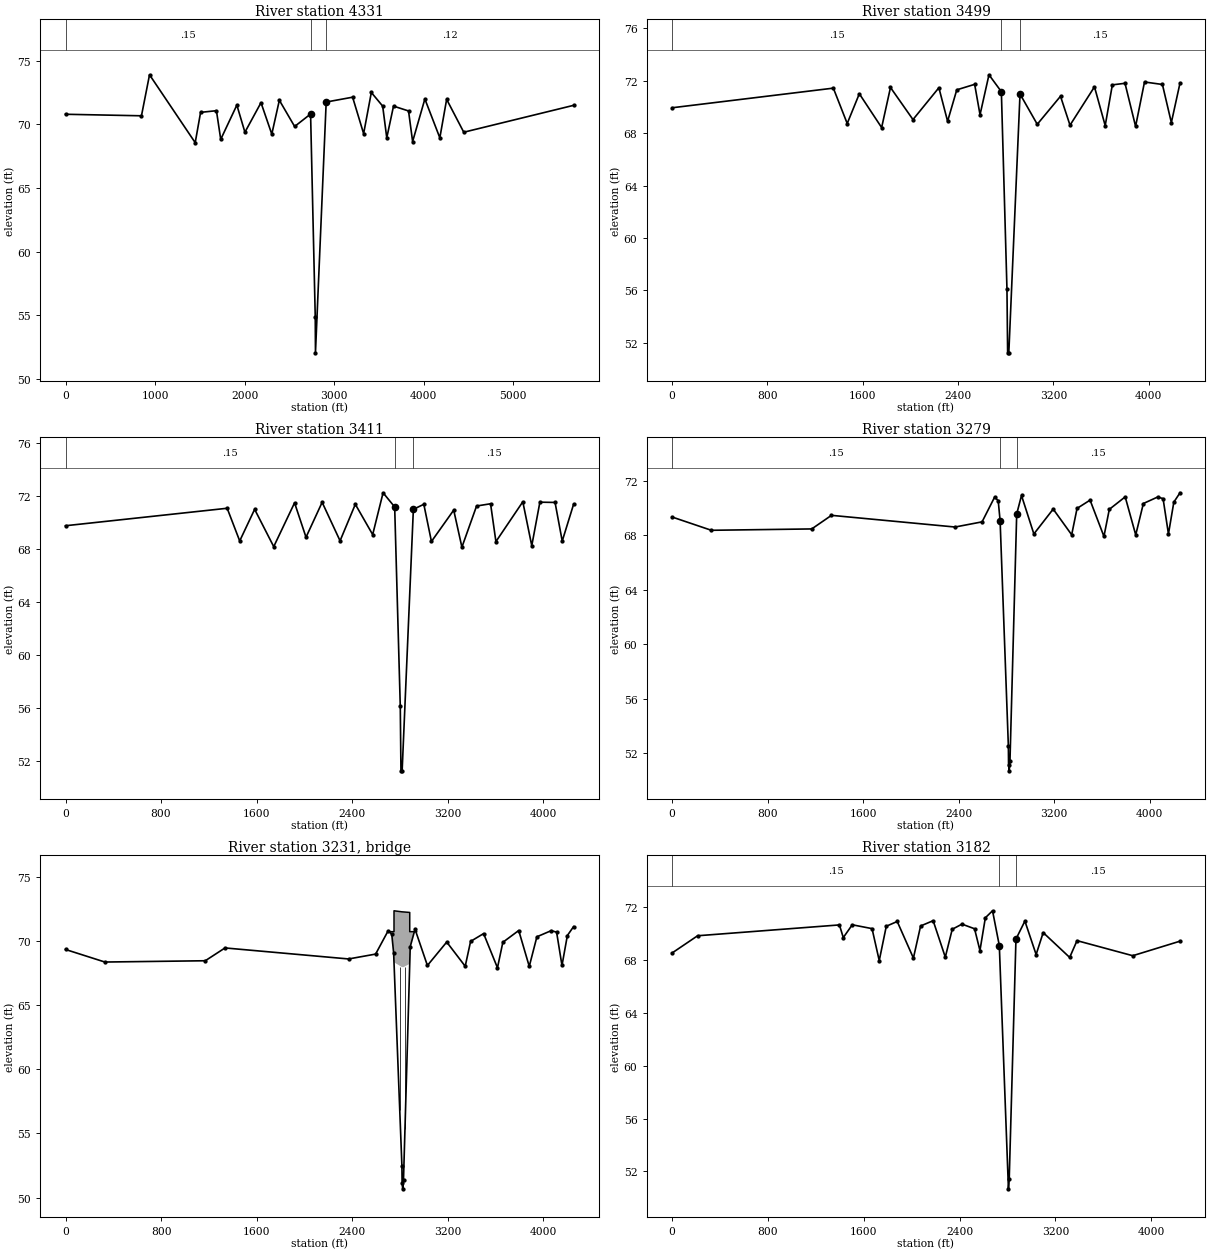
Type RM Length L Ch R = 1 ,4331    ,827.76,831.16,828.15
BEGIN DESCRIPTION:
4330.875
END DESCRIPTION:
XS GIS Cut Line= 4
       3055783.5    13819380.537     3055851.411    13816660.293
     3055851.411    13816470.169     3056296.307    13813743.754
#Sta/Elev= 30
       0   70.79   848.3   70.67  938.33   73.89 1448.49   68.56 1508.51   70.94
  1685.5   71.07 1733.58   68.82 1913.63   71.51 2003.66   69.38 2183.23    71.7
 2303.75   69.23 2388.18   71.89 2558.83   69.83 2736.97   70.81  2789.1   54.87
  2791.5   52.06 2911.22   71.75  3206.3   72.13 3329.34   69.27 3415.36    72.5
 3542.12   71.43 3587.72   68.94 3663.09   71.43 3830.89   71.05 3876.49   68.65
 4013.27   71.99 4180.45   68.94 4256.45   71.96  4447.6   69.38 5673.69   71.49
#Mann= 3 , 0 , 0
       0     .15       0 2736.97     .04       0 2911.22     .12       0
#XS Ineff= 2 , 0
       0    2713            2918       0
Permanent Ineff=
       T       T
Bank Sta=2736.97,2911.22
XS Rating Curve= 0
Exp/Cntr=.3,.1

Type RM Length L Ch R = 1 ,3499    ,91.08,88.14,85.93
BEGIN DESCRIPTION:
3499.713
END DESCRIPTION:
XS GIS Cut Line= 4
     3056586.699    13819435.604     3056678.635    13816704.116
     3056684.481    13816517.127     3056695.006    13815174.823
#Sta/Elev= 30
       0   69.94 1353.87   71.44 1470.28   68.74 1571.92   71.01  1759.1   68.43
 1833.27   71.49 2022.03   69.04 2239.37   71.47 2312.43   68.91 2389.46   71.31
 2539.54   71.73 2584.57   69.41 2659.61   72.46  2763.6   71.17 2810.52   56.11
  2816.2   51.23  2826.1   51.23 2920.11   70.99 3064.75   68.68 3259.75   70.82
 3339.49   68.61 3544.76   71.54 3634.76   68.58 3694.77   71.69 3800.88   71.81
 3889.77   68.52  3964.6   71.91 4114.78   71.72 4189.78   68.81 4262.46   71.83
#Mann= 3 , 0 , 0
       0     .15       0  2763.6     .04       0 2920.11     .15       0
#XS Ineff= 2 , 0
       0    2752            2924       0
Permanent Ineff=
       T       T
Bank Sta=2763.6,2920.11
XS Rating Curve= 0
Exp/Cntr=.3,.1

Type RM Length L Ch R = 1 ,3411    ,131.55,131.9,131.88
BEGIN DESCRIPTION:
3411.576
END DESCRIPTION:
XS GIS Cut Line= 4
     3056681.348     13819435.58     3056769.635    13816706.094
     3056769.635    13816527.904     3056794.855     13815182.69
#Sta/Elev= 30
       0   69.75 1353.79   71.07 1458.84    68.6 1583.86   70.99 1743.77   68.17
 1918.22   71.48 2014.13   68.88  2149.2   71.52 2299.28   68.61 2427.04   71.37
 2572.41   69.08 2659.47   72.24  2756.6   71.17 2803.52   56.11  2809.2   51.23
  2819.1   51.23 2913.11   70.99 3000.67   71.37 3064.53   68.56 3251.02   70.93
 3319.58   68.13 3442.47   71.24 3559.62   71.41 3604.46   68.55 3829.67   71.56
 3904.68   68.24 3972.62   71.53 4099.72   71.51 4159.73   68.59 4254.55   71.36
#Mann= 3 , 0 , 0
       0     .15       0  2756.6     .04       0 2913.11     .15       0
#XS Ineff= 2 , 0
       0    2748            2921       0
Permanent Ineff=
       T       T
Bank Sta=2756.6,2913.11
XS Rating Curve= 0
Exp/Cntr=.5,.3

Type RM Length L Ch R = 1 ,3279    ,95.79,97.75,99.61
BEGIN DESCRIPTION:
3279.675
END DESCRIPTION:
XS GIS Cut Line= 4
     3056802.443    13819431.911     3056901.385    13816708.243
     3056901.385    13816529.568        3056929.    13815180.717
#Sta/Elev= 30
       0   69.36  329.63   68.38 1170.18   68.48 1335.29   69.48 2369.99   68.62
 2596.12      69 2701.19   70.82 2731.21   70.56 2747.09   69.09 2816.27    52.5
 2817.87   51.13 2823.22   50.68 2829.65   51.39 2886.03   69.58 2926.21   70.94
 3029.78   68.11  3191.5   69.94  3346.3   68.05 3391.31   69.99 3500.24    70.6
 3616.36   67.93 3661.37   69.92 3794.29   70.84  3882.5   68.04 3946.42   70.35
 4066.45   70.83 4111.46   70.71 4156.47   68.11 4201.48   70.45 4253.27   71.14
#Mann= 3 , 0 , 0
       0     .15       0 2747.09     .04       0 2886.03     .15       0
#XS Ineff= 2 , 0
       0    2737            2904       0
Permanent Ineff=
       T       T
Bank Sta=2747.09,2886.03
XS Rating Curve= 0
Exp/Cntr=.5,.3

Type RM Length L Ch R = 3 ,3231    ,,,
BEGIN DESCRIPTION:
Wilcrest Bridge
END DESCRIPTION:
Bridge Culvert--1,0,-1,-1, 0
Deck Dist Width WeirC Skew NumUp NumDn MinLoCord MaxHiCord MaxSubmerge Is_Ogee
5,70,2.6,0, 7, 7, , , .95, 0, 0,0,,
    2710 2750.13 2750.13    2816 2881.88 2881.88    2940
   70.75   70.75   72.38    72.3   72.25   70.75   70.75
       0           68.03   67.99   67.95               0
    2700 2734.13 2734.13    2800 2865.88 2865.88    2890
   70.75   70.75   72.38    72.3   72.25   70.75   70.75
                   68.03   67.99   67.95       0
Pier Skew, UpSta & Num, DnSta & Num=  ,2798.05, 2 ,2782.05, 2 , 0 , 0 , 0 ,,
    1.35    1.35
     -.4   68.03
    1.35    1.35
     -.4   68.03
Pier Skew, UpSta & Num, DnSta & Num=  ,2841.96, 2 ,2825.96, 2 , 0 , 0 , 0 ,,
    1.35    1.35
       0   68.43
    1.35    1.35
       0   68.43
BR Coef=-1 , 1 , 1 ,1.25, 0 ,,,.8,-1,2,0,
WSPro=,,,, 1 ,,,, 0 ,,,, 0 ,,,,-1 ,-1 ,-1 , 0 , 0 , 0 , 0 , 0
BC Design=,, 0 ,, 0 ,,,,,,

Type RM Length L Ch R = 1 ,3182    ,115.89,114.06,112.54
BEGIN DESCRIPTION:
3181.926
END DESCRIPTION:
XS GIS Cut Line= 4
     3056898.958    13819421.266      3056997.17    13816709.912
     3057001.103    13816531.029     3057025.666    13815183.053
#Sta/Elev= 30
       0   68.52  213.91   69.83 1397.63   70.65  1429.7   69.69 1504.75   70.66
 1669.86   70.37  1729.9   67.95 1788.73   70.55    1880   70.91 2015.09   68.14
 2075.13   70.57 2179.83   70.97 2281.23   68.21 2339.17   70.32 2420.35   70.71
 2525.42   70.36 2570.45   68.71 2615.48   71.19 2675.52   71.72 2732.09   69.09
 2808.22   50.68 2814.65   51.39 2871.03   69.58  2945.6   70.94 3039.33   68.41
 3098.26   70.07 3319.27   68.19 3380.67   69.46 3845.75   68.32 4240.26   69.42
#Mann= 3 , 0 , 0
       0     .15       0 2732.09     .04       0 2871.03     .15       0
#XS Ineff= 2 , 0
       0    2721            2879       0
Permanent Ineff=
       T       T
Bank Sta=2732.09,2871.03
XS Rating Curve= 0
Exp/Cntr=.5,.3

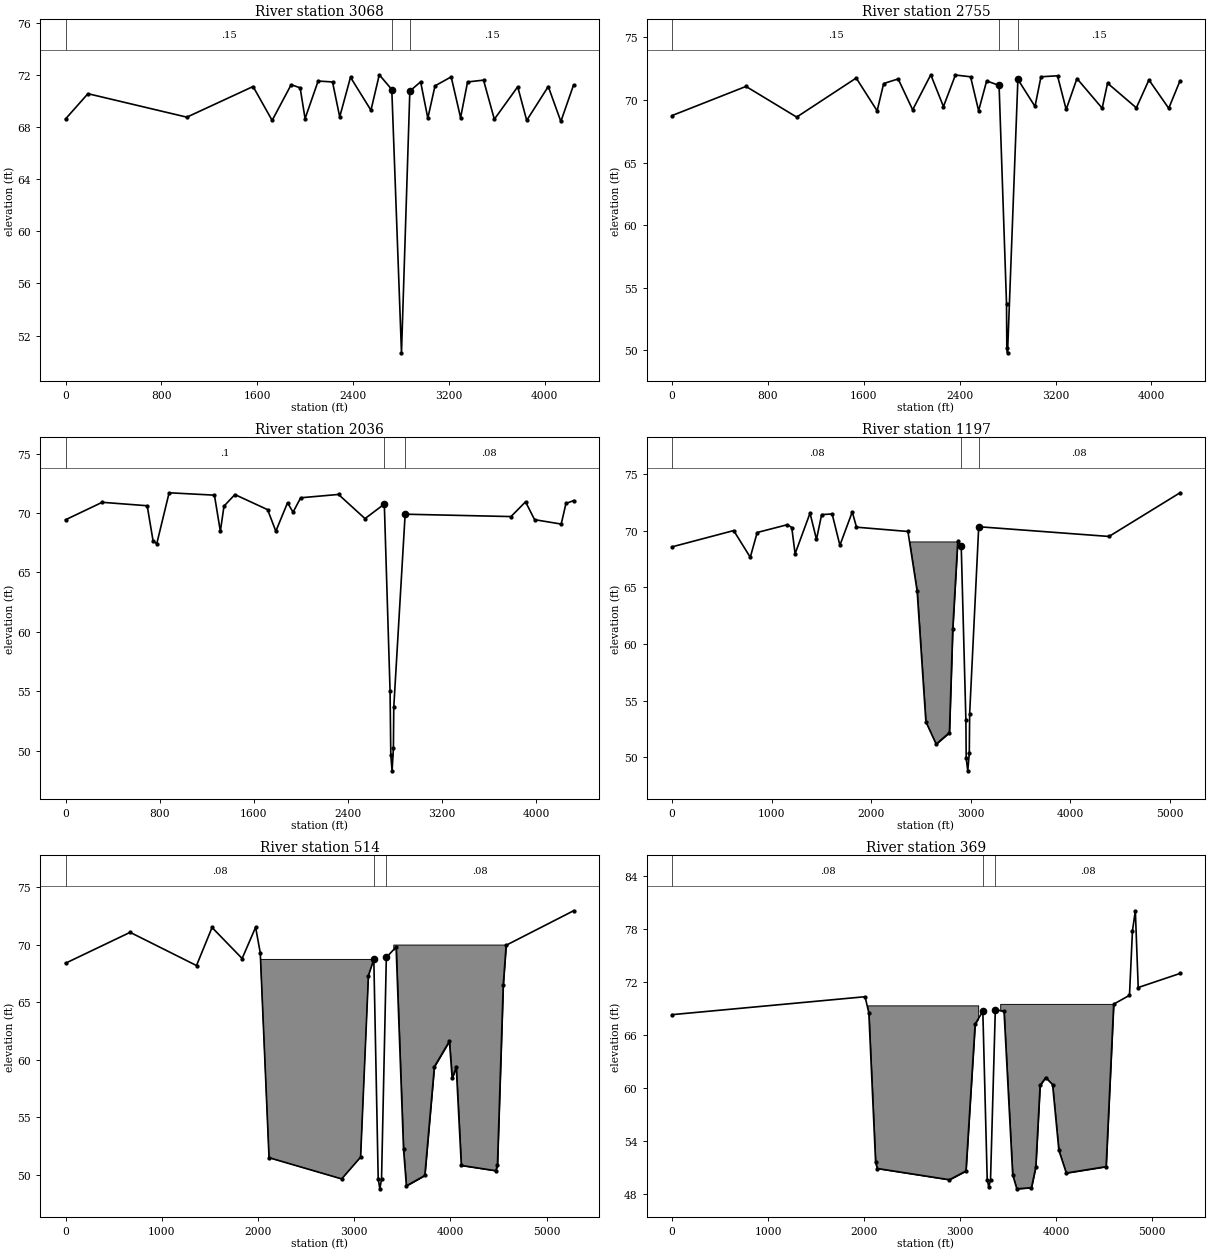
Type RM Length L Ch R = 1 ,3068    ,307.67,312.88,314.71
BEGIN DESCRIPTION:
3067.869
END DESCRIPTION:
XS GIS Cut Line= 4
     3057011.607    13819424.572     3057113.135    13816711.698
     3057113.135    13816532.243     3057149.944    13815186.635
#Sta/Elev= 30
       0   68.61   187.2   70.55 1012.78   68.75 1565.51    71.1 1724.67    68.5
 1883.39   71.24 1958.44      71 1999.58   68.64 2108.55   71.52 2228.63   71.45
 2288.67   68.77 2378.74   71.81  2549.4   69.28  2618.9      72 2723.34   70.87
 2804.22   50.68 2873.97   70.75    2964   71.46 3024.02   68.67 3084.04   71.15
 3219.09   71.84 3297.46   68.71 3355.89   71.45 3489.19   71.59 3579.23   68.59
  3774.3   71.08 3849.33    68.5  4029.4    71.1 4134.44   68.42 4240.34   71.21
#Mann= 3 , 0 , 0
       0     .15       0 2723.34     .04       0 2873.97     .15       0
#XS Ineff= 2 , 0
       0    2718            2880       0
Permanent Ineff=
       T       T
Bank Sta=2723.34,2873.97
XS Rating Curve= 0
Exp/Cntr=.3,.1

Type RM Length L Ch R = 1 ,2755    ,714.61,718.52,714.6
BEGIN DESCRIPTION:
2754.993
END DESCRIPTION:
XS GIS Cut Line= 5
     3057110.685    13819417.233      3057171.34    13818758.844
     3057424.862    13816729.425     3057426.772    13816550.016
     3057479.388    13815198.471
#Sta/Elev= 30
       0   68.75  617.34   71.08 1040.45   68.63 1536.88   71.75 1711.57   69.13
 1766.04   71.31 1886.98   71.68 2007.91   69.21 2159.07   72.01 2264.89   69.47
 2364.63   71.99 2490.97   71.85 2558.16   69.14 2625.35   71.52 2728.97   71.16
 2790.98   53.71  2793.5   50.17 2799.57    49.8 2885.79   71.64 3028.59   69.48
 3078.45   71.85 3216.42   71.93 3288.61   69.24 3378.68   71.71 3588.84   69.34
 3633.87   71.34 3874.05   69.37 3979.13    71.6 4144.26   69.33 4238.36   71.53
#Mann= 3 , 0 , 0
       0     .15       0 2728.97     .04       0 2885.79     .15       0
#XS Ineff= 2 , 0
       0    2720            2886       0
Permanent Ineff=
       T       T
Bank Sta=2728.97,2885.79
XS Rating Curve= 0
Exp/Cntr=.3,.1

Type RM Length L Ch R = 1 ,2036    ,824.68,839.26,852.37
BEGIN DESCRIPTION:
2036.470
END DESCRIPTION:
XS GIS Cut Line= 4
     3057492.064    13819450.259     3058124.393    13816853.403
     3058124.393    13816641.658     3058263.723    13815218.199
#Sta/Elev= 30
       0   69.43  311.61    70.9  693.76   70.61  743.42   67.67  774.75   67.41
  879.99    71.7 1264.86    71.5 1315.09   68.46 1345.97   70.58  1438.6   71.55
 1716.49   70.28  1786.3   68.47 1885.62   70.86 1932.62   70.07 1997.35   71.28
 2318.58   71.56 2543.62   69.53 2707.64   70.75 2756.39   55.05 2762.69   49.67
 2773.59   48.33 2784.81   50.24 2787.89   53.67 2884.48    69.9 3783.45    69.7
    3907   70.94 3983.87   69.44 4209.94   69.07  4250.2    70.8 4314.74   71.04
#Mann= 3 , 0 , 0
       0      .1       0 2707.64     .04       0 2884.48     .08       0
#XS Ineff= 2 , 0
       0    2654            2957       0
Permanent Ineff=
       T       T
Bank Sta=2707.64,2884.48
XS Rating Curve= 0
Exp/Cntr=.3,.1

Type RM Length L Ch R = 1 ,1197    ,630.2,683.09,668.95
BEGIN DESCRIPTION:
1197.207
END DESCRIPTION:
XS GIS Cut Line= 4
     3057712.491    13819450.259      3058964.32    13816862.141
     3058962.387    13816661.176     3059612.887    13814743.695
#Sta/Elev= 30
       0   68.58  619.58   70.02   786.2   67.66  855.59   69.85 1158.81   70.54
 1202.76   70.29 1236.09   67.97 1386.05   71.56 1450.81   69.24 1502.69   71.43
 1608.03   71.49 1685.98   68.72 1810.18   71.67  1852.6   70.32 2369.14   69.94
 2461.55   64.67 2549.26   53.12  2652.4   51.15  2785.7   52.17 2819.03   61.32
 2869.01   69.06 2904.03   68.68 2951.01   53.25 2954.06   49.91 2969.68   48.79
  2985.1   50.34  2988.8   53.85 3079.82   70.36 4387.81    69.5 5100.76   73.36
#Mann= 3 , 0 , 0
       0     .08       0 2904.03     .04       0 3079.82     .08       0
#XS Ineff= 2 , 0
       0    2574            3294       0
Permanent Ineff=
       T       T
#Block Obstruct= 1 ,-1
 2186.26 2867.83   69.06
Bank Sta=2904.03,3079.82
XS Rating Curve= 0
Exp/Cntr=.3,.1

Type RM Length L Ch R = 1 ,514     ,104.57,144.46,144.13
BEGIN DESCRIPTION:
514.116
END DESCRIPTION:
XS GIS Cut Line= 5
     3057811.569    13819461.267     3059443.489    13817106.769
     3059646.386    13816885.686     3059646.386    13816664.033
     3059755.081     13814772.97
#Sta/Elev= 30
       0   68.38   671.7   71.06 1361.59   68.18 1523.28   71.48 1835.88   68.79
 1976.01    71.5 2024.33   69.28 2115.59   51.51 2870.61   49.67 3067.36   51.56
 3148.79   67.31 3204.72   68.71 3250.29   49.68 3267.45   48.81 3284.87   49.65
 3334.71   68.88 3436.35   69.79 3513.22   52.28 3543.27   49.07 3734.72   49.97
 3834.18   59.41 3990.47   61.62 4018.88    58.4 4061.51   59.36 4114.21   50.84
 4473.54   50.38 4489.83    50.9 4549.93   66.49 4579.98   69.94 5280.67   72.93
#Mann= 3 , 0 , 0
       0     .08       0 3204.72     .04       0 3334.71     .08       0
#XS Ineff= 2 , 0
       0    2665            3561       0
Permanent Ineff=
       T       T
#Block Obstruct= 2 ,-1
 2006.28 3204.85   68.71 3407.11 4675.38      70
Bank Sta=3204.72,3334.71
XS Rating Curve= 0
Exp/Cntr=.3,.1

Type RM Length L Ch R = 1 ,369     ,107.77,94.47,94.06
BEGIN DESCRIPTION:
369.653
END DESCRIPTION:
XS GIS Cut Line= 5
     3057917.986    13819475.945     3059609.922    13817050.667
      3059790.83    13816873.991      3059790.83    13816666.037
     3059884.727    13814798.063
#Sta/Elev= 30
       0   68.33 2009.94   70.36  2049.1   68.54 2119.68   51.61 2137.97   50.93
 2887.83   49.66  3060.2   50.65 3155.66   67.27 3235.72   68.71 3281.29   49.68
 3298.45   48.81 3315.87   49.65 3365.71   68.88 3456.54   68.72 3546.65   50.21
 3589.75   48.63  3741.9   48.76 3786.95    51.1 3832.01   60.33 3890.05   61.22
 3961.55   60.43 4027.26   52.99 4104.55   50.42 4519.26   51.14 4597.98   69.52
 4762.36   70.52 4793.22   77.81 4823.26   80.08  4853.3    71.4 5288.28   72.99
#Mann= 3 , 0 , 0
       0     .08       0 3235.72     .04       0 3365.71     .08       0
#XS Ineff= 2 , 0
       0    2639            3582       0
Permanent Ineff=
       T       T
#Block Obstruct= 2 ,-1
 2015.56  3187.2   69.38  3416.6 4820.05   69.55
Bank Sta=3235.72,3365.71
XS Rating Curve= 0
Exp/Cntr=.5,.3