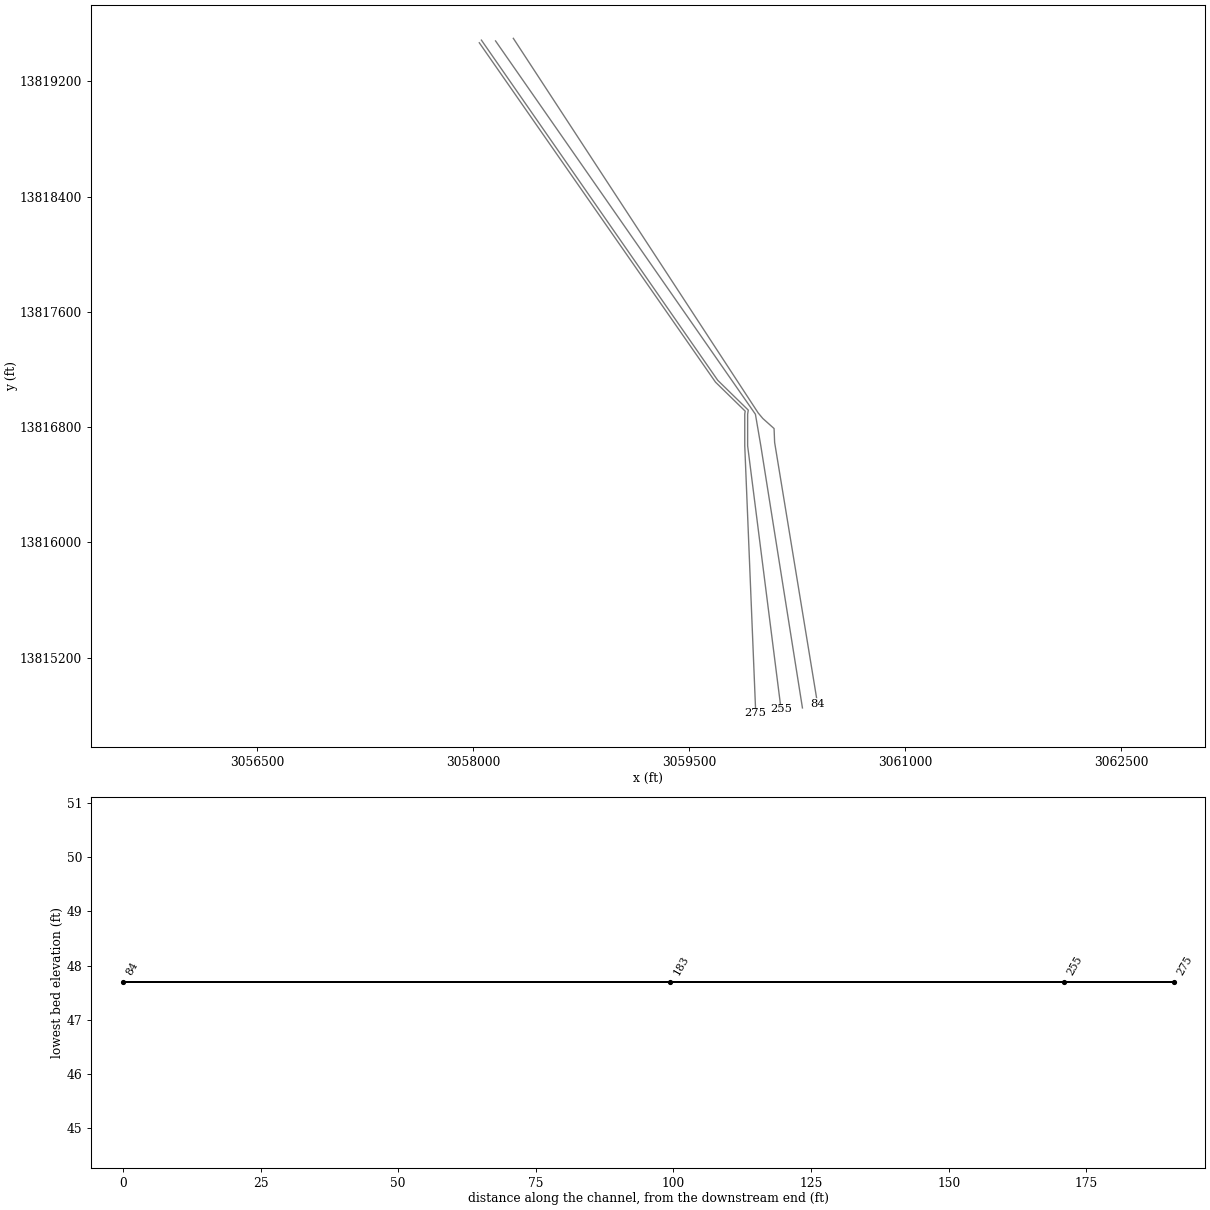
HEC-RAS study D122-00-00.prj: D122-00-00

--- D122-00-00.g04 (geometry) --- (continued)

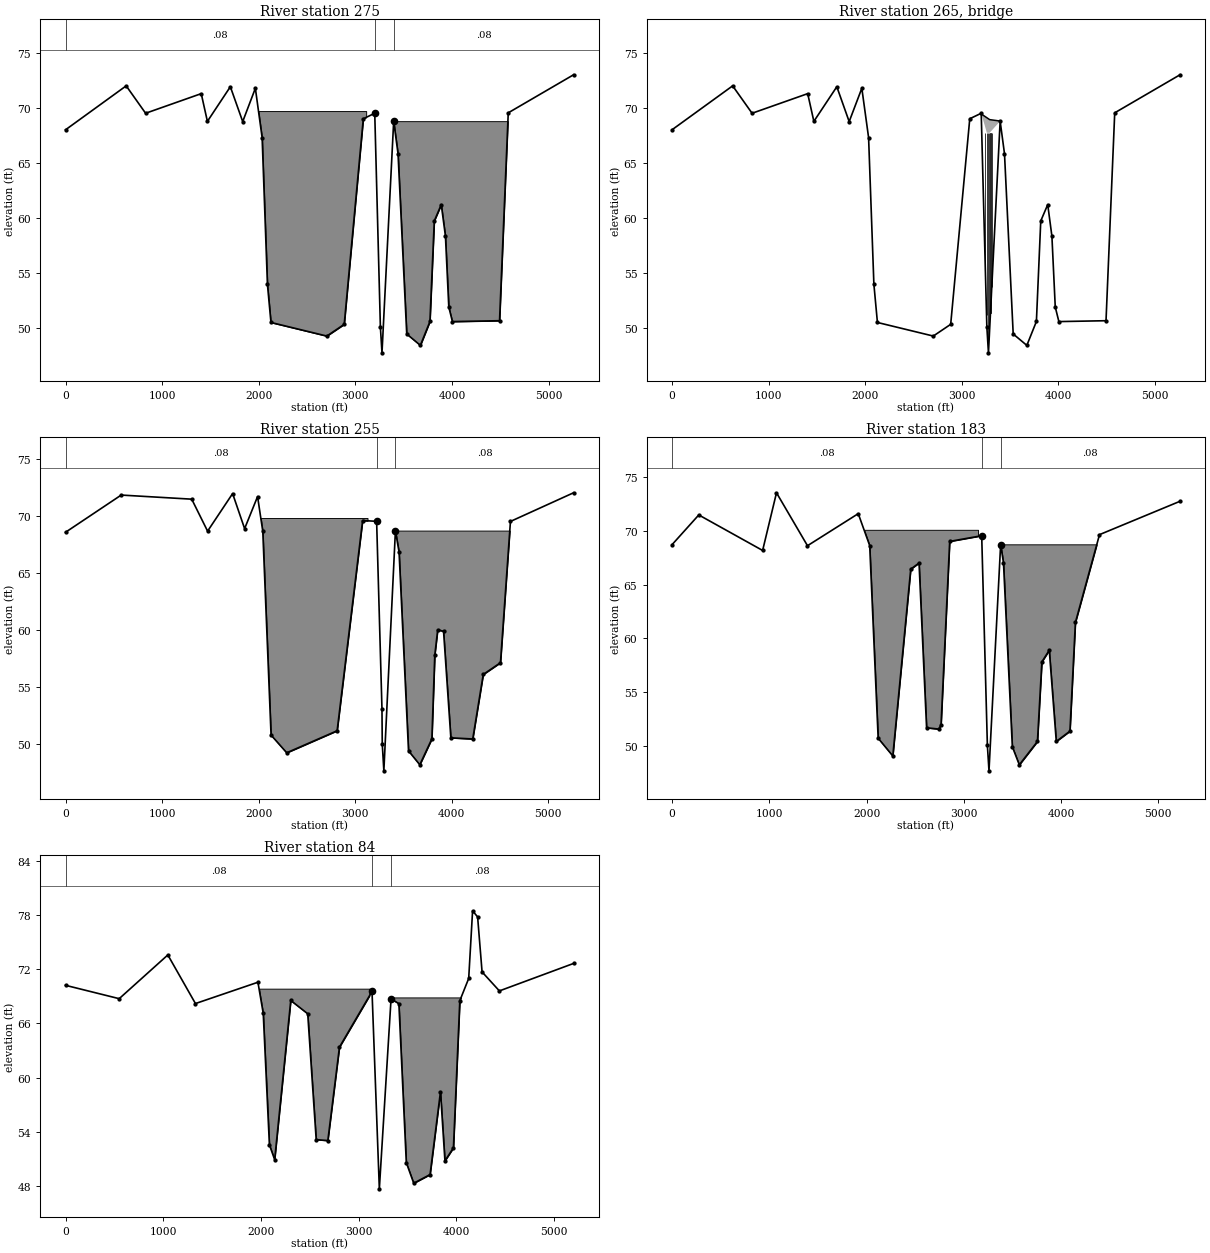
Type RM Length L Ch R = 1 ,275     ,21.8,20,24.82
BEGIN DESCRIPTION:
275.182
END DESCRIPTION:
XS GIS Cut Line= 6
     3058042.199    13819468.055     3059682.295    13817111.685
     3059888.382    13816910.418     3059885.278    13816890.602
     3059885.278    13816668.949     3059961.546    13814812.149
#Sta/Elev= 30
       0   68.03  628.14   72.04  829.18   69.54 1405.04   71.33 1468.83    68.8
 1706.41   71.96 1834.34   68.78 1965.37   71.82 2035.37   67.32  2090.2   53.94
 2126.75   50.46 2705.02   49.22 2885.22   50.29 3082.67   69.04 3201.19   69.54
 3259.52   50.06 3276.12   47.69 3397.18   68.82 3442.21   65.85 3532.29   49.41
 3673.44   48.37 3772.49   50.55 3817.53   59.72 3889.74   61.21    3933   58.33
 3967.66   51.87 4005.11   50.54  4493.1   50.62 4583.18   69.58  5259.1   73.05
#Mann= 3 , 0 , 0
       0     .08       0 3201.19     .04       0 3397.18     .08       0
#XS Ineff= 2 , 0
       0    2581            3566       0
Permanent Ineff=
       T       T
#Block Obstruct= 2 ,-1
  1960.5 3112.39   69.74 3397.78 4748.41   68.82
Bank Sta=3201.19,3397.18
XS Rating Curve= 0
Exp/Cntr=.5,.3

Type RM Length L Ch R = 3 ,265     ,,,
BEGIN DESCRIPTION:
Footbridge
END DESCRIPTION:
Bridge Culvert--1,0,-1,-1, 0
Deck Dist Width WeirC Skew NumUp NumDn MinLoCord MaxHiCord MaxSubmerge Is_Ogee
5,10,2.6,0, 3, 3, , , .95, 0, 0,0,,
 3201.19 3288.69  3397.2
   69.48   68.96   68.83
   67.76   67.76   67.76
 3223.21 3310.69 3417.87
   69.49   68.96   68.69
   67.76   67.76   67.76
Pier Skew, UpSta & Num, DnSta & Num=  ,3242.77, 2 ,3264.77, 2 , 0 , 0 , 0 ,,
     .83     .83
     -.3   67.76
     .83     .83
     -.3   67.76
Pier Skew, UpSta & Num, DnSta & Num=  ,3256.34, 2 ,3278.34, 2 , 0 , 0 , 0 ,,
     .83     .83
       0   68.06
     .83     .83
       0   68.06
Pier Skew, UpSta & Num, DnSta & Num=  ,3269.91, 2 ,3291.91, 2 , 0 , 0 , 0 ,,
     .83     .83
       0   68.06
     .83     .83
       0   68.06
Pier Skew, UpSta & Num, DnSta & Num=  ,3283.48, 2 ,3305.48, 2 , 0 , 0 , 0 ,,
     .83     .83
       0   68.06
     .83     .83
       0   68.06
Pier Skew, UpSta & Num, DnSta & Num=  ,3297.05, 2 ,3319.05, 2 , 0 , 0 , 0 ,,
     .83     .83
       0   68.06
     .83     .83
       0   68.06
Pier Skew, UpSta & Num, DnSta & Num=  ,3310.62, 2 ,3332.62, 2 , 0 , 0 , 0 ,,
     .83     .83
       0   68.06
     .83     .83
       0   68.06
BR Coef=-1 , 1 , 1 ,1.25, 0 ,,,.8,-1,2,0,
WSPro=,,,, 1 ,,,, 0 ,,,, 0 ,,,,-1 ,-1 ,-1 , 0 , 0 , 0 , 0 , 0
BC Design=,, 0 ,, 0 ,,,,,,

Type RM Length L Ch R = 1 ,255     ,56.19,71.5,93.22
BEGIN DESCRIPTION:
255.177
END DESCRIPTION:
XS GIS Cut Line= 6
     3058056.877    13819486.402     3059697.648    13817124.647
     3059909.738    13816917.517     3059905.278    13816889.045
     3059905.278    13816669.678     3060137.196    13814841.424
#Sta/Elev= 30
       0   68.58  577.04   71.84 1307.62   71.48 1472.01   68.68 1731.21   71.97
 1855.56    68.9 1989.87   71.71 2043.75   68.67 2129.53   50.82 2291.63   49.27
 2814.16    51.2 3078.23   69.61 3223.19   69.54 3278.56   53.14 3281.52   50.06
 3298.12   47.69 3417.88   68.72 3455.65   66.85 3553.64   49.44 3670.34   48.22
 3795.56   50.49  3825.8   57.82 3856.04   60.04 3916.53   59.91 3992.13   50.58
 4218.93   50.48 4327.82   56.13 4506.21   57.16  4609.6   69.53 5263.31   72.04
#Mann= 3 , 0 , 0
       0     .08       0 3223.19     .04       0 3417.88     .08       0
#XS Ineff= 2 , 0
       0    2592            3587       0
Permanent Ineff=
       T       T
#Block Obstruct= 2 ,-1
 1985.07 3128.86   69.83  3414.9 4790.55   68.73
Bank Sta=3223.19,3417.88
XS Rating Curve= 0
Exp/Cntr=.5,.3

Type RM Length L Ch R = 1 ,183     ,27.34,99.4,99.97
BEGIN DESCRIPTION:
183.680
END DESCRIPTION:
XS GIS Cut Line= 4
     3058155.059    13819480.836     3059959.282    13816888.925
     3059996.557    13816671.254     3060285.751    13814849.982
#Sta/Elev= 30
       0    68.7  275.58   71.47  931.96   68.17 1074.52   73.53 1393.07   68.61
 1915.01   71.59 2032.74   68.62 2119.74   50.72 2270.33   49.07 2454.78   66.44
 2539.99      67 2617.58   51.69 2743.59   51.57 2766.27   51.97 2855.17   69.01
 3184.19   69.54 3242.52   50.06 3259.12   47.69 3378.88   68.72 3407.99   67.03
 3499.12   49.93 3570.85   48.25 3757.32   50.42 3802.88   57.82 3878.82    58.9
 3950.94   50.42 4091.45   51.38 4147.54   61.48 4395.21   69.64 5222.97   72.74
#Mann= 3 , 0 , 0
       0     .08       0 3184.19     .04       0 3378.88     .08       0
#XS Ineff= 2 , 0
       0    2549            3560       0
Permanent Ineff=
       T       T
#Block Obstruct= 2 ,-1
 1897.17 3146.03   70.09  3378.9 4545.31   68.74
Bank Sta=3184.19,3378.88
XS Rating Curve= 0
Exp/Cntr=.3,.1

Type RM Length L Ch R = 1 ,84      ,23.85,84.28,50.04
BEGIN DESCRIPTION:
84.279
END DESCRIPTION:
XS GIS Cut Line= 6
     3058278.503    13819498.829     3059978.264    13816898.334
     3060010.252    13816859.983     3060088.834    13816789.671
     3060092.643    13816693.675     3060390.604    13814878.903
#Sta/Elev= 30
       0   70.22   549.3   68.74 1046.92   73.58 1329.55    68.2 1968.92   70.56
  2023.1   67.12 2086.28   52.56 2140.04   50.92 2304.86   68.54 2478.25   67.07
 2564.94   53.14 2684.14   53.03 2803.08   63.38 3136.19   69.54 3211.12   47.69
 3330.88   68.72 3410.98   68.19 3486.99   50.59 3562.99   48.31  3730.2   49.27
 3836.61   58.43 3882.21   50.79 3969.35   52.23 4034.63   68.52 4125.42   70.98
  4165.2   78.47 4216.63   77.79 4262.23    71.7  4439.4    69.6 5198.19   72.64
#Mann= 3 , 0 , 0
       0     .08       0 3136.19     .04       0 3330.88     .08       0
#XS Ineff= 2 , 0
       0    2502            3578       0
Permanent Ineff=
       T       T
#Block Obstruct= 2 ,-1
 1908.02 3109.36   69.85 3350.95 4192.05   68.88
Bank Sta=3136.19,3330.88
XS Rating Curve= 0
Exp/Cntr=.3,.1

Chan Stop Cuts=-1